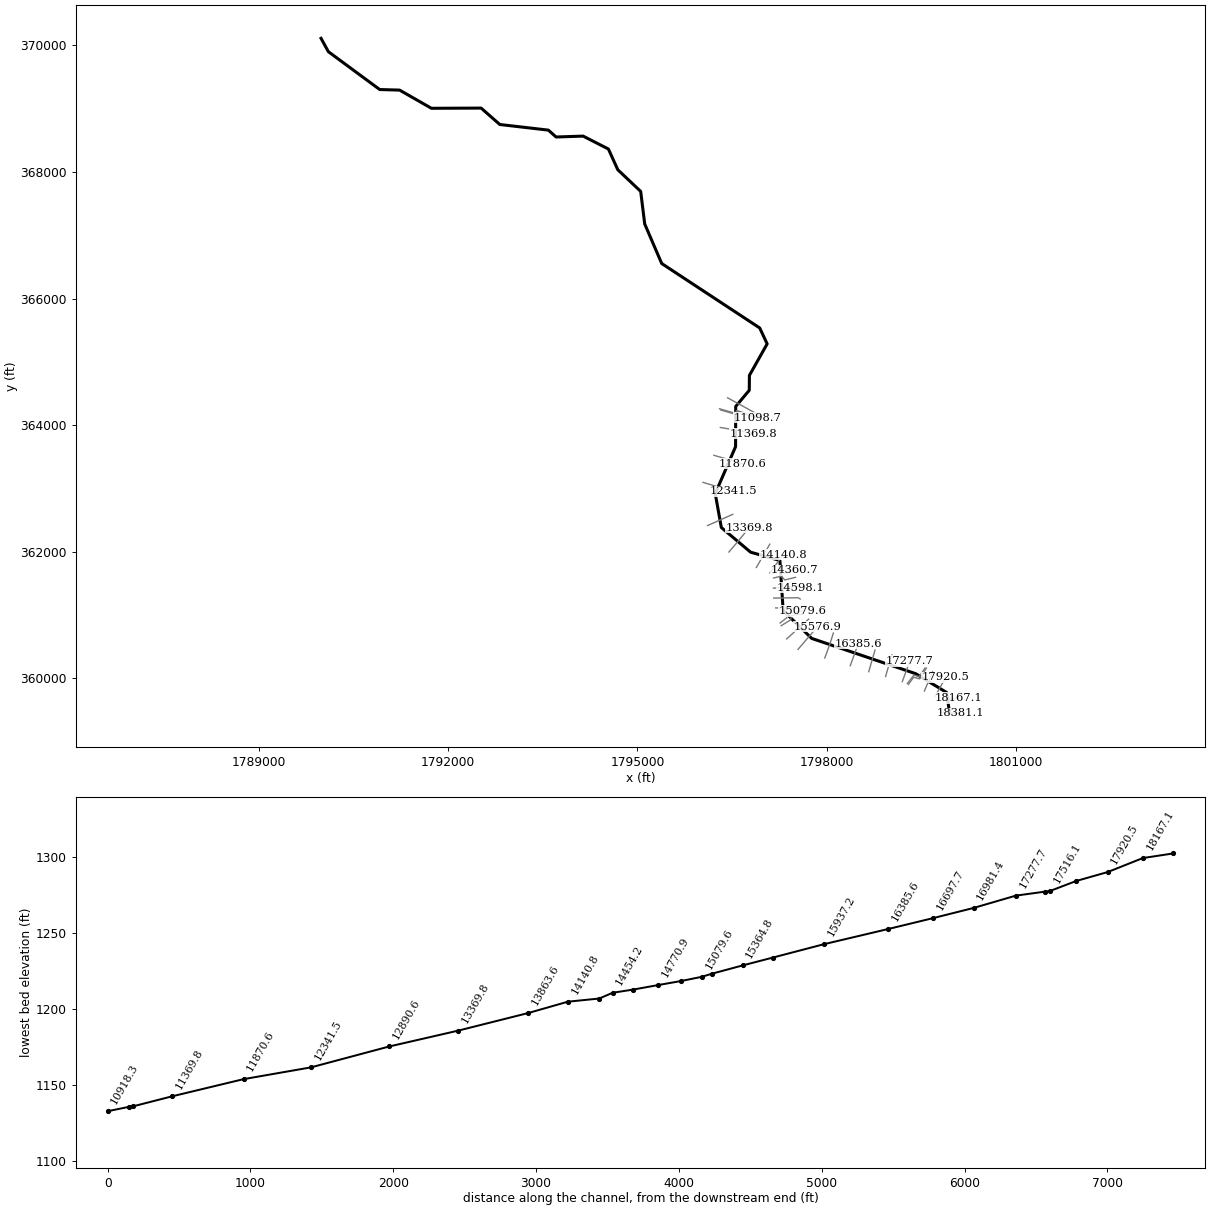
--- LOGANFK.prj (project) ---

Proj Title=LOGANFK
Current Plan=p01
Default Exp/Contr=0,0
English Units
Geom File=g01
Flow File=f01
Plan File=p01
BEGIN DESCRIPTION:
END DESCRIPTION:
DSS Export Rating Curves= 0
DSS Export Rating Curve Sorted= 0
DSS Export Volume Flow Curves= 0
DXF OffsetX= 0
DXF OffsetY= 0
DXF ScaleX= 0
DXF ScaleY= 0

--- LOGANFK.p01 (plan) ---

Plan Title=Floodplain
Program Version=4.00
Geom File=g01
Flow File=f01
K Sum by GR=0
Std Step Tol=0.01
Critical Tol=0.01
Num of Std Step Trials=20
Max Error Tol=0.3
Flow Tol Ratio=0.001
Split Flow NTrial=30
Split Flow Tol=0.02
Split Flow Ratio=0.02
Log Output Level=0
Friction Slope Method=1
Unsteady Friction Slope Method=2
Unsteady Bridges Friction Slope Method=1
Global Log Level=0
CheckData=False
Run HTab=0
Run UNet=0
Run PostProcess=0
UNET Theta=0
UNET Theta Warmup=0
UNET ZTol=0
UNET ZSATol=0
UNET MxIter=0
UNET MaxInSteps=0
UNET DtIC=0
UNET DtMin=0
UNET MaxCRTS=0
UNET WFStab=0
UNET SFStab=0
UNET WFX=0
UNET SFX=0
UNET DSS MLevel=0
UNET DZMax Abort=0
UNET Convert EG Bridges=0
UNET Use Existing IB Tables=0
UNET Froude Limit=0
UNET Froude Power=0
Write IC File=0
Echo Input=False
Echo Output=False
Write Detailed=0

--- LOGANFK.f01 (steady flow) ---

Flow Title=NFF Regression Equation
Program Version=4.00
Number of Profiles=1
Profile Names=P100yr
River Rch & RM=LOGANFK,Main      ,18381.1
948.9778
River Rch & RM=LOGANFK,Main      ,15149.8
1037.151
River Rch & RM=LOGANFK,Main      ,11870.6
1152.254
River Rch & RM=LOGANFK,Main      ,8942.2
1280.197
River Rch & RM=LOGANFK,Main      ,3218.8
1592.966
River Rch & RM=LOGANFK,Main      ,3218.8
1404.635
River Rch & RM=LOGANFK,Main      ,433.3
1650.786
River Rch & RM=LOGANFK,Main      ,63.2
1651.980
Boundary for River Rch & Prof#=LOGANFK,Main      ,1
Up Type=0
Dn Type=3
Dn Slope=0.02286

--- LOGANFK.g01 (geometry) ---

Geom Title=USGS 10m DEM
Program Version=4.10

River Reach=LOGANFK         ,Main
Reach XY= 30
     1799944.249      359449.788     1799897.006      359775.861
     1799408.196       360072.49       1797760.2      360630.288
     1797308.811      361070.305     1797257.075      361860.956
     1796792.984      361992.492     1796329.472       362382.22
     1796232.901      362918.461     1796555.166      363659.781
     1796557.336      364295.197      1796772.18      364550.405
      1796774.35      364785.866     1797055.383      365283.478
      1796937.11      365535.214     1795385.461       366553.01
     1795116.364      367177.467     1795052.345      367692.766
     1794689.932      368034.563     1794541.277      368362.254
     1794140.886      368566.248     1793712.284      368552.142
     1793590.756      368660.648     1792821.442      368749.624
     1792525.218      369008.956     1791738.543      369005.701
     1791233.985      369293.244     1790919.315      369301.925
     1790106.598      369899.798     1789990.173      370111.002

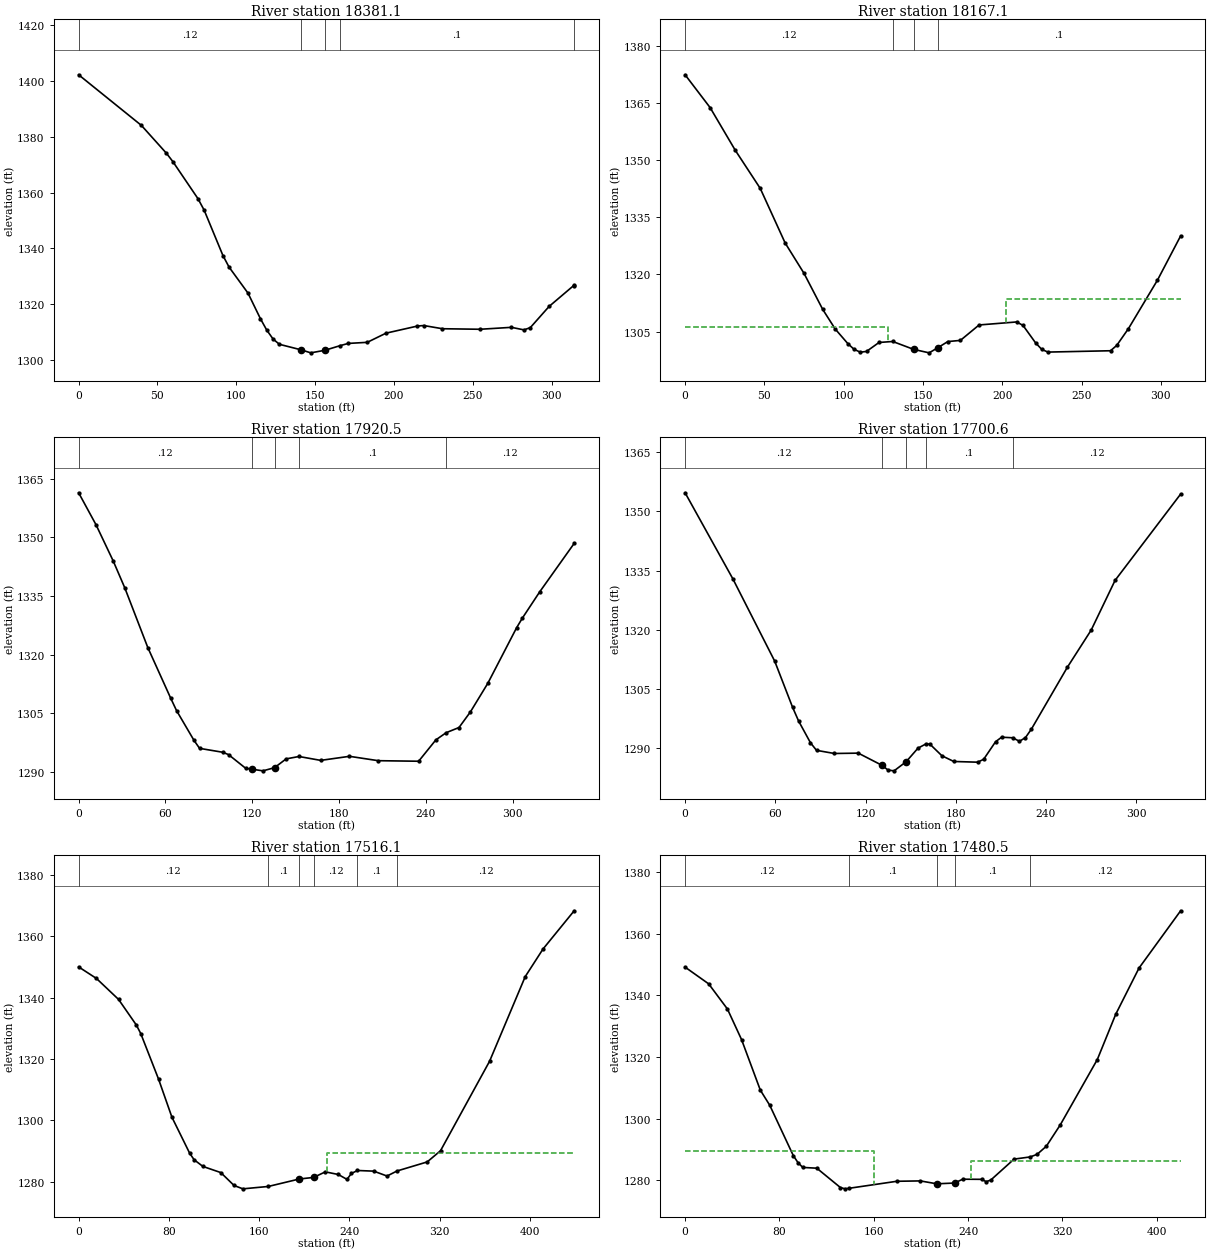
Type RM Length L Ch R = 1 ,18381.1 ,208.9,214,218.5
XS GIS Cut Line= 2
     1799796.288      359463.597     1800109.978      359445.624
#Sta/Elev= 30
       0 1402.28    39.8 1384.11    55.7  1374.1    59.7 1371.16    75.6 1357.88
    79.6 1353.69    91.5 1337.41    95.4 1333.25   107.4 1323.92   115.3 1314.71
   119.3 1310.64   123.3 1307.45   127.3 1305.56   141.1 1303.57   147.2  1302.5
   156.1 1303.41  165.98 1305.11     171 1305.88     183 1306.27   194.9 1309.56
   214.8 1312.11   218.8  1312.3   230.7 1311.15   254.6 1310.96   274.4 1311.65
   282.4 1310.74   286.4 1311.56   298.3 1319.15   313.91326.646   314.2 1326.78
#Mann= 5 ,-1 , 0
       0     .12       0   141.1    .045       0   156.1     .12       0
  165.98      .1       0   313.9     .12       0
Bank Sta=141.1,156.1
XS Rating Curve= 0 ,0
Exp/Cntr=0.3,0.1

Type RM Length L Ch R = 1 ,18167.1 ,225.7,246.6,267.8
XS GIS Cut Line= 3
     1799773.502      359643.067     1800042.599        359684.3
     1800082.746      359687.555
#Sta/Elev= 30
       0 1372.35    15.8 1363.73    31.6 1352.58    47.4 1342.55    63.1 1328.24
      75 1320.28    86.8 1310.82    94.7 1305.67   102.6 1301.87   106.5 1300.38
   110.5 1299.61   114.4 1299.81   122.3 1302.16  130.931302.417   144.2 1300.34
   153.9 1299.44   159.2 1300.74   165.7  1302.4   173.6  1302.7   185.4 1306.75
   209.1 1307.54   213.1 1306.63     221 1302.07   224.9 1300.35   228.8 1299.64
   268.3 1299.99   272.2 1301.39   279.6  1305.8   297.9 1318.51   312.5  1330.1
#Mann= 4 ,-1 , 0
       0     .12       0  130.93      .1       0   144.2    .045       0
   159.2      .1       0
#XS Ineff= 2 , 0
          128.01 1306.29   202.4         1313.57
Permanent Ineff=
       F       F
Bank Sta=144.2,159.2
XS Rating Curve= 0 ,0
Exp/Cntr=0.3,0.1

Type RM Length L Ch R = 1 ,17920.5 ,217.6,219.9,221
XS GIS Cut Line= 2
     1799716.644      359718.371      1799884.83      360016.765
#Sta/Elev= 30
       0 1361.45      12 1353.27    23.9 1343.98    31.9 1337.09    47.8  1321.8
    63.7 1308.76    67.7 1305.62    79.7 1298.03    83.6 1295.96    99.6 1294.96
   103.6 1294.36   115.5 1290.84   119.5 1290.63   127.4  1290.2   135.4 1291.01
   143.4 1293.26   152.31293.875   167.3 1292.88   187.2 1293.92   207.1  1292.8
     235 1292.66   246.9 1298.13  254.011299.972   262.9  1301.3   270.8 1305.31
   282.8 1312.62   302.7 1326.86   306.7 1329.34   318.6 1336.02   342.5 1348.48
#Mann= 5 ,-1 , 0
       0     .12       0   119.5    .045       0   135.4     .12       0
   152.3      .1       0  254.01     .12       0
Bank Sta=119.5,135.4
XS Rating Curve= 0 ,0
Exp/Cntr=0.3,0.1

Type RM Length L Ch R = 1 ,17700.6 ,219.8,184.5,144.7
XS GIS Cut Line= 2
     1799544.986      359798.232     1799673.892      360101.618
#Sta/Elev= 30
       0 1354.72    31.8 1332.91    59.6  1312.1    71.5 1300.41    75.5 1296.94
    83.4 1291.43    87.4 1289.52    99.3 1288.72   115.2 1288.81   131.1  1285.7
     135 1284.52     139 1284.33     147 1286.63   154.9 1290.07  160.041291.114
   162.8  1291.1   170.8 1288.15   178.7  1286.7   194.6 1286.52   198.6 1287.26
   206.5  1291.7   210.5 1292.84  217.851292.703   222.4 1291.81   226.4 1292.75
   230.4 1294.93   254.2 1310.52   270.1 1319.96     286 1332.55   329.6 1354.39
#Mann= 5 ,-1 , 0
       0     .12       0   131.1    .045       0     147     .12       0
  160.04      .1       0  217.85     .12       0
Bank Sta=131.1,147
XS Rating Curve= 0 ,0
Exp/Cntr=0.3,0.1

Type RM Length L Ch R = 1 ,17516.1 ,40.7,35.6,35.6
XS GIS Cut Line= 4
     1799291.514      359902.182     1799375.411      360016.418
      1799468.12      359990.897     1799576.887      360160.429
#Sta/Elev= 30
       0 1349.97    15.8  1346.2    35.4 1339.38    51.2 1331.02    55.1 1328.24
    70.9 1313.38    82.7 1301.03    98.4 1289.32   102.4 1287.16   110.2 1284.99
     126    1283   137.8 1278.79   145.6  1277.7  168.091278.472   195.6  1280.9
  208.34 1281.42   218.7 1283.23   230.2 1282.37   237.9 1280.78   241.8 1282.71
  247.211283.674   261.6 1283.46   273.4 1281.87   282.3 1283.52     309 1286.46
   320.8  1290.1   364.3 1319.24   395.9  1346.8   411.7  1355.8   439.3 1368.24
#Mann= 6 ,-1 , 0
       0     .12       0  168.09      .1       0   195.6    .045       0
  208.34     .12       0  247.21      .1       0   282.3     .12       0
#XS Ineff= 2 , 0
                          220.18         1289.29
Permanent Ineff=
       F       F
Bank Sta=195.6,208.34
XS Rating Curve= 0 ,0
Exp/Cntr=0.3,0.1

Type RM Length L Ch R = 1 ,17480.5 ,163,202.8,239.3
XS GIS Cut Line= 4
     1799276.323      359919.543      1799380.49      360050.837
     1799459.917      360023.927     1799556.271      360162.599
#Sta/Elev= 30
       0 1349.12      20  1343.7    35.9 1335.55    47.9 1325.63    63.8 1309.27
    71.8 1304.36    91.8 1288.03    95.8 1285.75    99.8 1284.22   111.7 1283.97
   131.7 1277.71   135.7 1277.28   138.81277.443   179.6 1279.73   199.5 1279.85
   213.5 1278.91   228.5 1279.16   235.5  1280.4   251.5 1280.36   255.4  1279.6
   259.3 1280.14     279 1286.91  292.721287.617   298.6 1288.47   306.4 1291.09
   318.2    1298   349.6 1319.16   365.3 1333.89     385 1348.82   420.3 1367.38
#Mann= 5 ,-1 , 0
       0     .12       0   138.8      .1       0   213.5    .045       0
   228.5      .1       0  292.72     .12       0
#XS Ineff= 2 , 0
          160.26 1289.43  242.51         1286.14
Permanent Ineff=
       F       F
Bank Sta=213.5,228.5
XS Rating Curve= 0 ,0
Exp/Cntr=0.3,0.1

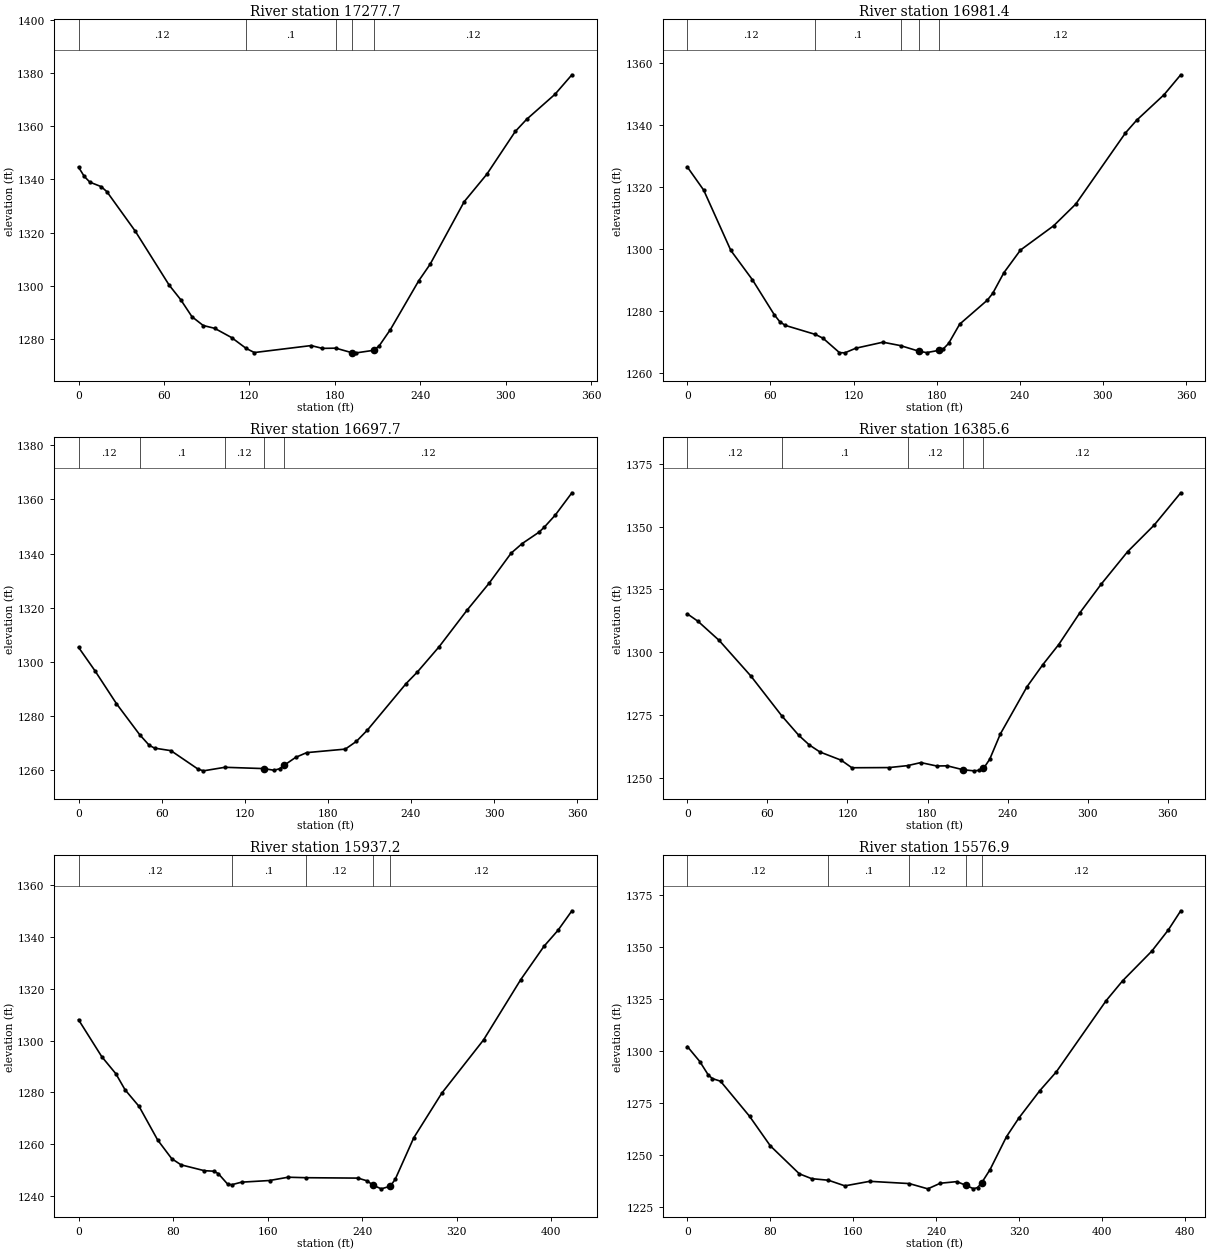
Type RM Length L Ch R = 1 ,17277.7 ,294.5,296.2,297.9
XS GIS Cut Line= 2
     1799195.396       359947.32     1799315.231      360272.557
#Sta/Elev= 30
       0 1344.65       4 1341.18       8 1338.98    15.9 1337.31    19.9 1335.42
    39.8 1320.57    63.7 1300.16    71.7 1294.76    79.7 1288.27    87.6 1284.96
    95.6 1283.91   107.6 1280.39  117.761276.329   123.5 1274.77   163.4  1277.4
   171.3 1276.34  180.721276.422   192.3 1274.67   195.2 1274.66   207.3 1275.61
   211.2 1277.29   219.1 1283.44     239 1301.83     247 1308.06   270.9 1331.61
   286.8 1341.96   306.8 1358.09   314.7 1362.63   334.7 1372.11   346.6 1379.46
#Mann= 5 ,-1 , 0
       0     .12       0  117.76      .1       0  180.72     .12       0
   192.3    .045       0   207.3     .12       0
Bank Sta=192.3,207.3
XS Rating Curve= 0 ,0
Exp/Cntr=0.3,0.1

Type RM Length L Ch R = 1 ,16981.4 ,283.6,283.7,283.7
XS GIS Cut Line= 3
      1798930.69      360028.063     1798976.466      360186.256
     1799030.508      360369.994
#Sta/Elev= 30
       0 1326.41    11.8 1318.96    31.4 1299.52      47 1290.06    62.7 1278.85
    66.7 1276.58    70.6 1275.39   92.481272.455      98 1271.22   109.8  1266.6
   113.7 1266.53   121.6 1268.02   141.2 1269.96  153.981268.848   166.9 1267.09
   172.7  1266.6   181.9 1267.36   184.6 1267.73   188.6 1269.55   196.6 1275.77
   216.6 1283.52   220.5 1285.73   228.5 1292.34   240.5 1299.65   264.4 1307.46
   280.4 1314.46   316.3  1337.4   324.3 1341.46   344.2 1349.73   356.2 1356.13
#Mann= 5 ,-1 , 0
       0     .12       0   92.48      .1       0  153.98     .12       0
   166.9    .045       0   181.9     .12       0
Bank Sta=166.9,181.9
XS Rating Curve= 0 ,0
Exp/Cntr=0.3,0.1

Type RM Length L Ch R = 1 ,16697.7 ,313.7,312.1,310.6
XS GIS Cut Line= 3
     1798663.763      360104.018     1798709.539      360262.211
     1798763.581      360445.949
#Sta/Elev= 30
       0 1305.42    11.8 1296.82    27.4 1284.61   44.171273.159      51 1269.28
    54.9 1268.21    66.7 1267.28    86.3 1260.46    90.2 1259.83  105.661261.139
   133.7 1260.66   141.2 1260.04   145.1  1260.6   148.7 1261.97   156.8 1264.81
   164.7 1266.55   192.6 1267.85   200.6  1270.7   208.6  1274.9   236.5 1292.04
   244.5 1296.24   260.4 1305.68   280.4 1319.07   296.4 1329.07   312.3 1340.17
   320.3 1343.72   332.3 1347.87   336.2 1349.73   344.2 1354.24   356.2 1362.46
#Mann= 5 ,-1 , 0
       0     .12       0   44.17      .1       0  105.66     .12       0
   133.7    .045       0   148.7     .12       0
Bank Sta=133.7,148.7
XS Rating Curve= 0 ,0
Exp/Cntr=0.3,0.1

Type RM Length L Ch R = 1 ,16385.6 ,447.6,448.4,449.5
XS GIS Cut Line= 2
     1798371.457      360197.963     1798496.809      360545.845
#Sta/Elev= 30
       0 1315.26       8 1312.29    23.9 1304.65    47.7 1290.43   70.831274.585
    83.5 1266.86    91.4 1263.02    99.4 1260.21   115.3 1256.94   123.3 1253.93
   151.1    1254  165.011254.772     175 1255.99   186.9 1254.63   194.8  1254.7
   206.6 1253.14   214.7  1252.7   218.7 1252.89   221.6 1253.85   222.7 1254.22
   226.6  1257.3   234.6 1267.41   254.5 1286.16   266.4    1295   278.3 1303.01
   294.2  1315.7   310.1 1327.05     330 1340.07   349.9 1350.65   369.8 1363.52
#Mann= 5 ,-1 , 0
       0     .12       0   70.83      .1       0  165.01     .12       0
   206.6    .045       0   221.6     .12       0
Bank Sta=206.6,221.6
XS Rating Curve= 0 ,0
Exp/Cntr=0.3,0.1

Type RM Length L Ch R = 1 ,15937.2 ,368.5,360.3,350.7
XS GIS Cut Line= 3
     1797967.794      360319.975     1798051.569      360549.649
     1798103.931      360714.794
#Sta/Elev= 30
       0 1308.09    19.7  1293.8    31.6 1287.22    39.4 1281.01    51.3 1274.56
      67  1261.6    78.9 1254.38    86.8    1252   106.5 1249.74   114.4 1249.54
   118.3 1248.62   126.2 1244.56   129.71244.309     138  1245.3   161.7 1245.94
   177.4 1247.21  192.581247.023   236.6 1246.87   244.5 1245.78   248.9 1244.22
   256.3 1242.72   263.9 1243.74   268.1  1246.4   283.8 1262.45   307.5 1279.69
   342.9  1300.3   374.4 1323.62   394.1 1336.51   405.9 1342.66   417.7 1350.21
#Mann= 5 ,-1 , 0
       0     .12       0   129.7      .1       0  192.58     .12       0
   248.9    .045       0   263.9     .12       0
Bank Sta=248.9,263.9
XS Rating Curve= 0 ,0
Exp/Cntr=0.3,0.1

Type RM Length L Ch R = 1 ,15576.9 ,215,212.1,208.8
XS GIS Cut Line= 2
     1797543.628      360456.805     1797853.873      360817.505
#Sta/Elev= 30
       0 1302.22      12 1295.01      20 1288.69      24 1286.85      32 1285.54
      60 1268.69      80 1254.51     108 1241.06   119.9 1238.74  136.091237.975
   151.9 1235.28   175.9 1237.46  214.011236.378   231.9 1233.85   243.9 1236.54
   259.9 1237.32   268.7 1235.51   275.9 1233.92   279.9 1234.47   283.7 1236.66
   291.9 1243.09   307.8 1258.95   319.8 1267.94   339.8 1280.96   355.8 1290.04
   403.8 1324.21   419.8 1333.82   447.8 1347.99   463.8 1358.21   475.8 1367.42
#Mann= 5 ,-1 , 0
       0     .12       0  136.09      .1       0  214.01     .12       0
   268.7    .045       0   283.7     .12       0
Bank Sta=268.7,283.7
XS Rating Curve= 0 ,0
Exp/Cntr=0.3,0.1

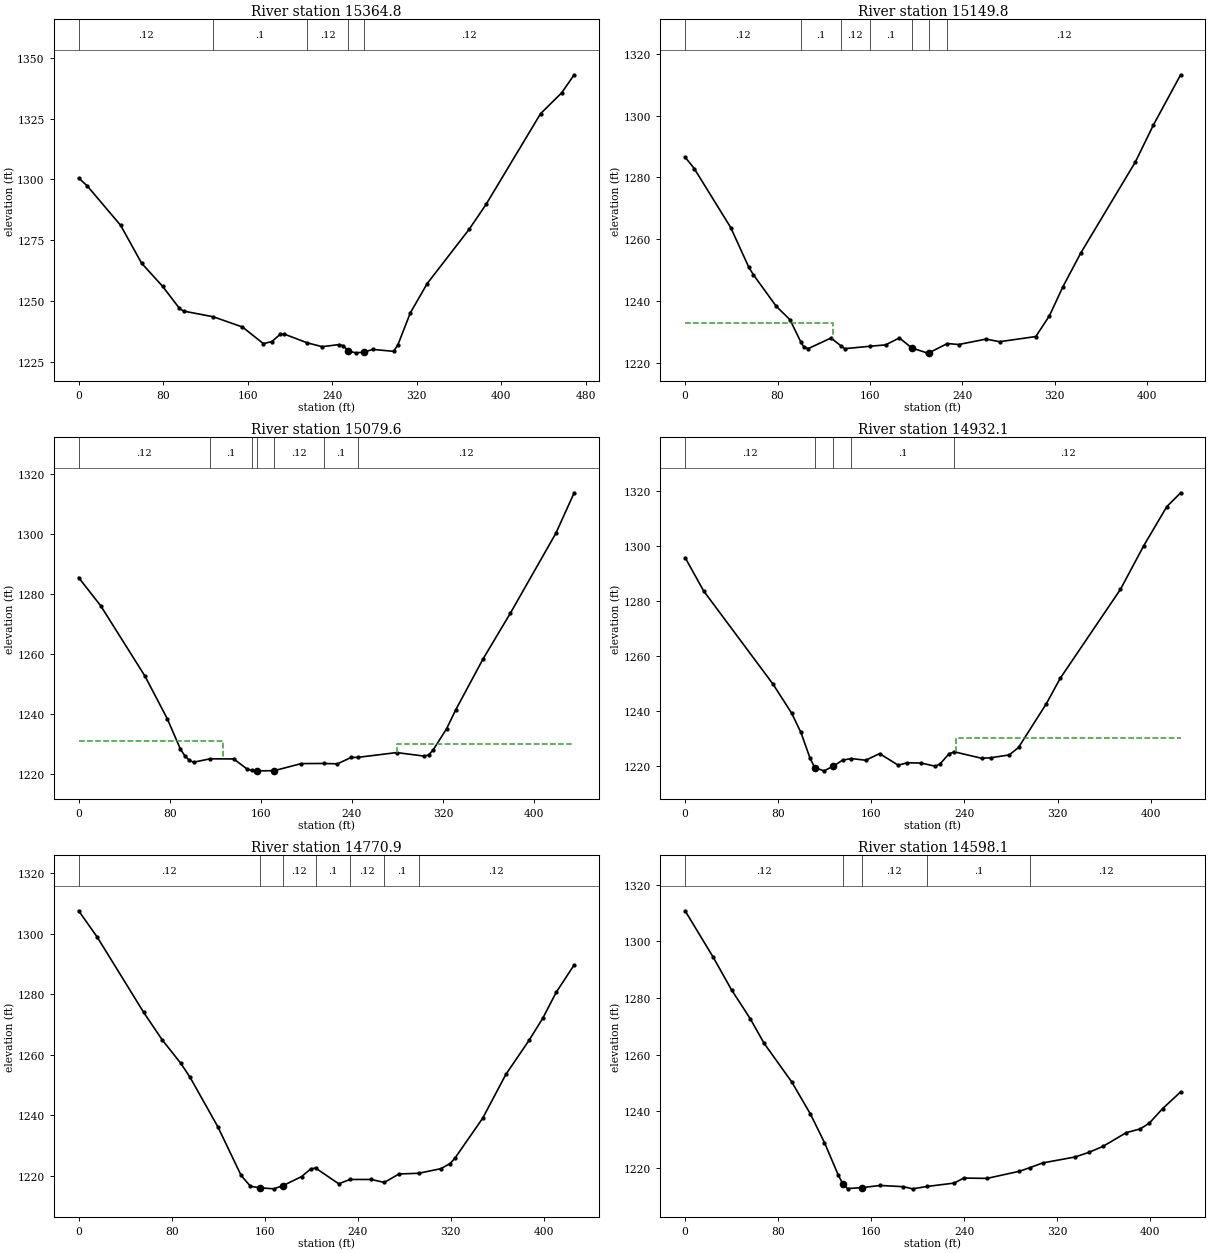
Type RM Length L Ch R = 1 ,15364.8 ,201,215.1,229.1
XS GIS Cut Line= 2
     1797364.019       360622.65     1797713.371      360935.422
#Sta/Elev= 30
       0 1300.54       8 1297.38    39.7 1281.12    59.6  1265.5    79.5 1255.99
    95.4 1246.94    99.3 1245.83  127.46 1243.48     155 1239.29   174.8 1232.45
   182.8 1233.28   190.7 1236.28   194.7 1236.35  216.021232.808   230.5 1231.19
   246.4 1232.06   250.4 1231.56   255.3  1229.4   262.3 1228.66   270.3 1228.96
   278.2 1230.06     298 1229.29     302 1231.86   313.9 1245.11   329.8 1257.13
   369.6 1279.51   385.5 1289.68   437.1 1327.01     457 1335.55   468.9    1343
#Mann= 5 ,-1 , 0
       0     .12       0  127.46      .1       0  216.02     .12       0
   255.3    .045       0   270.3     .12       0
Bank Sta=255.3,270.3
XS Rating Curve= 0 ,0
Exp/Cntr=0.3,0.1

Type RM Length L Ch R = 1 ,15149.8 ,69.5,70.1,71.3
XS GIS Cut Line= 4
     1797277.393      360830.715      1797425.31      360921.687
     1797443.366      360994.604     1797622.243      361016.765
#Sta/Elev= 30
       0  1286.6     7.9 1282.91    39.5 1263.78    55.2 1250.89    59.2 1248.46
    78.9 1238.28    90.8 1233.94  100.311226.617   102.6 1225.22   106.6 1224.57
   126.3    1228  134.981225.446   138.1 1224.55  159.791225.319   173.6 1225.78
   185.5 1228.03   196.2 1224.79   209.2  1223.2   211.2 1223.22  227.021226.205
   236.9  1225.9   260.5 1227.65   272.3 1226.81   303.6 1228.48   315.4  1235.2
   327.1 1244.63   342.8  1255.7   389.8 1285.03   405.5 1297.06     429 1313.27
#Mann= 7 ,-1 , 0
       0     .12       0  100.31      .1       0  134.98     .12       0
  159.79      .1       0   196.2    .045       0   211.2      .1       0
  227.02     .12       0
#XS Ineff= 2 , 0
          127.76 1232.98
Permanent Ineff=
       F       F
Bank Sta=196.2,211.2
XS Rating Curve= 0 ,0
Exp/Cntr=0.3,0.1

Type RM Length L Ch R = 1 ,15079.6 ,179.3,147.5,115.2
XS GIS Cut Line= 4
      1797259.83      360873.536     1797364.558      360954.266
     1797380.704      361023.537     1797609.222      361062.338
#Sta/Elev= 30
       0  1285.5    19.4  1276.1    58.3 1252.66    77.8 1238.55    89.4 1228.37
    93.3 1226.16    97.2 1224.63   101.1 1224.03  115.351225.164   136.2 1225.12
     148 1221.75  151.981221.322   155.9 1221.16   156.7 1221.16   171.7 1221.21
   195.5 1223.57   215.21223.617   227.3 1223.49   239.3 1225.62  245.161225.643
   279.3 1227.24   303.3 1226.07   307.3 1226.42   311.3 1228.08   323.2 1235.21
   331.2 1241.48   355.2 1258.42   379.2 1273.66   419.2  1300.3   435.2 1313.72
#Mann= 7 ,-1 , 0
       0     .12       0  115.35      .1       0  151.98     .12       0
   156.7    .045       0   171.7     .12       0   215.2      .1       0
  245.16     .12       0
#XS Ineff= 2 , 0
          126.91 1231.07  279.25         1230.24
Permanent Ineff=
       F       F
Bank Sta=156.7,171.7
XS Rating Curve= 0 ,0
Exp/Cntr=0.3,0.1

Type RM Length L Ch R = 1 ,14932.1 ,161.9,161.2,161.6
XS GIS Cut Line= 2
     1797190.533      361111.599     1797616.326      361107.837
#Sta/Elev= 30
       0 1295.84    15.9 1283.72    75.6 1249.81    91.5 1239.33    99.5 1232.31
   107.4 1222.89   111.4  1219.5   119.4 1218.35   127.3 1220.02   135.3 1222.23
  142.781222.816   155.2  1222.2   167.1 1224.61   183.1 1220.41     191 1221.28
     203 1221.18   214.9 1220.02   218.9 1220.78   226.8 1224.54  231.391225.252
   254.7 1222.92   262.6 1223.09   278.6 1224.14   286.5 1226.84   310.4 1242.74
   322.3 1251.94   374.1  1284.3     394 1300.05   413.9 1314.32   425.8 1319.36
#Mann= 5 ,-1 , 0
       0     .12       0   111.4    .045       0   127.3     .12       0
  142.78      .1       0  231.39     .12       0
#XS Ineff= 2 , 0
                           232.9         1230.29
Permanent Ineff=
       F       F
Bank Sta=111.4,127.3
XS Rating Curve= 0 ,0
Exp/Cntr=0.3,0.1

Type RM Length L Ch R = 1 ,14770.9 ,170.2,172.8,174.2
XS GIS Cut Line= 3
     1797159.182      361267.443     1797550.382      361272.413
     1797578.488      361251.971
#Sta/Elev= 30
       0 1307.63      16 1298.92    55.9 1274.04    71.9 1264.91    87.8  1257.2
    95.8 1252.55   119.8  1236.1   139.7 1220.09   147.7 1216.52   155.7 1216.02
   167.7 1215.67   175.6 1216.72   191.6 1219.71   199.6 1222.27  203.681222.554
   223.6 1217.34  233.221218.766   251.5 1218.77  262.761217.789   275.5 1220.59
   292.31220.817   311.4 1222.34   319.4 1224.05   323.4 1225.76   347.3    1239
   367.3 1253.52   387.2 1264.78     399 1272.09   410.5 1280.63     426 1289.73
#Mann= 7 ,-1 , 0
       0     .12       0   155.7    .045       0   175.6     .12       0
  203.68      .1       0  233.22     .12       0  262.76      .1       0
   292.3     .12       0
Bank Sta=155.7,175.6
XS Rating Curve= 0 ,0
Exp/Cntr=0.3,0.1

Type RM Length L Ch R = 1 ,14598.1 ,165.9,143.9,121.7
XS GIS Cut Line= 3
     1797155.461      361424.068     1797545.722      361451.602
      1797574.96      361432.815
#Sta/Elev= 30
       0 1310.74      24 1294.48    39.9 1282.88    55.9 1272.76    67.9 1264.04
    91.8 1250.33   107.8 1239.05   119.8 1229.04   131.7 1217.57   135.7 1214.37
   139.7 1212.83   151.7 1213.15   167.7 1213.92   187.6 1213.49   195.6 1212.73
  207.911213.561   231.5 1214.77   239.5 1216.53   259.5 1216.41   287.4 1218.92
  296.741220.244   307.4 1221.86   335.3 1223.96   347.3 1225.62   359.3  1227.7
   379.2 1232.53   391.2 1233.85     399 1235.85   410.5 1241.01     426  1246.9
#Mann= 5 ,-1 , 0
       0     .12       0   135.7    .045       0   151.7     .12       0
  207.91      .1       0  296.74     .12       0
Bank Sta=135.7,151.7
XS Rating Curve= 0 ,0
Exp/Cntr=0.3,0.1

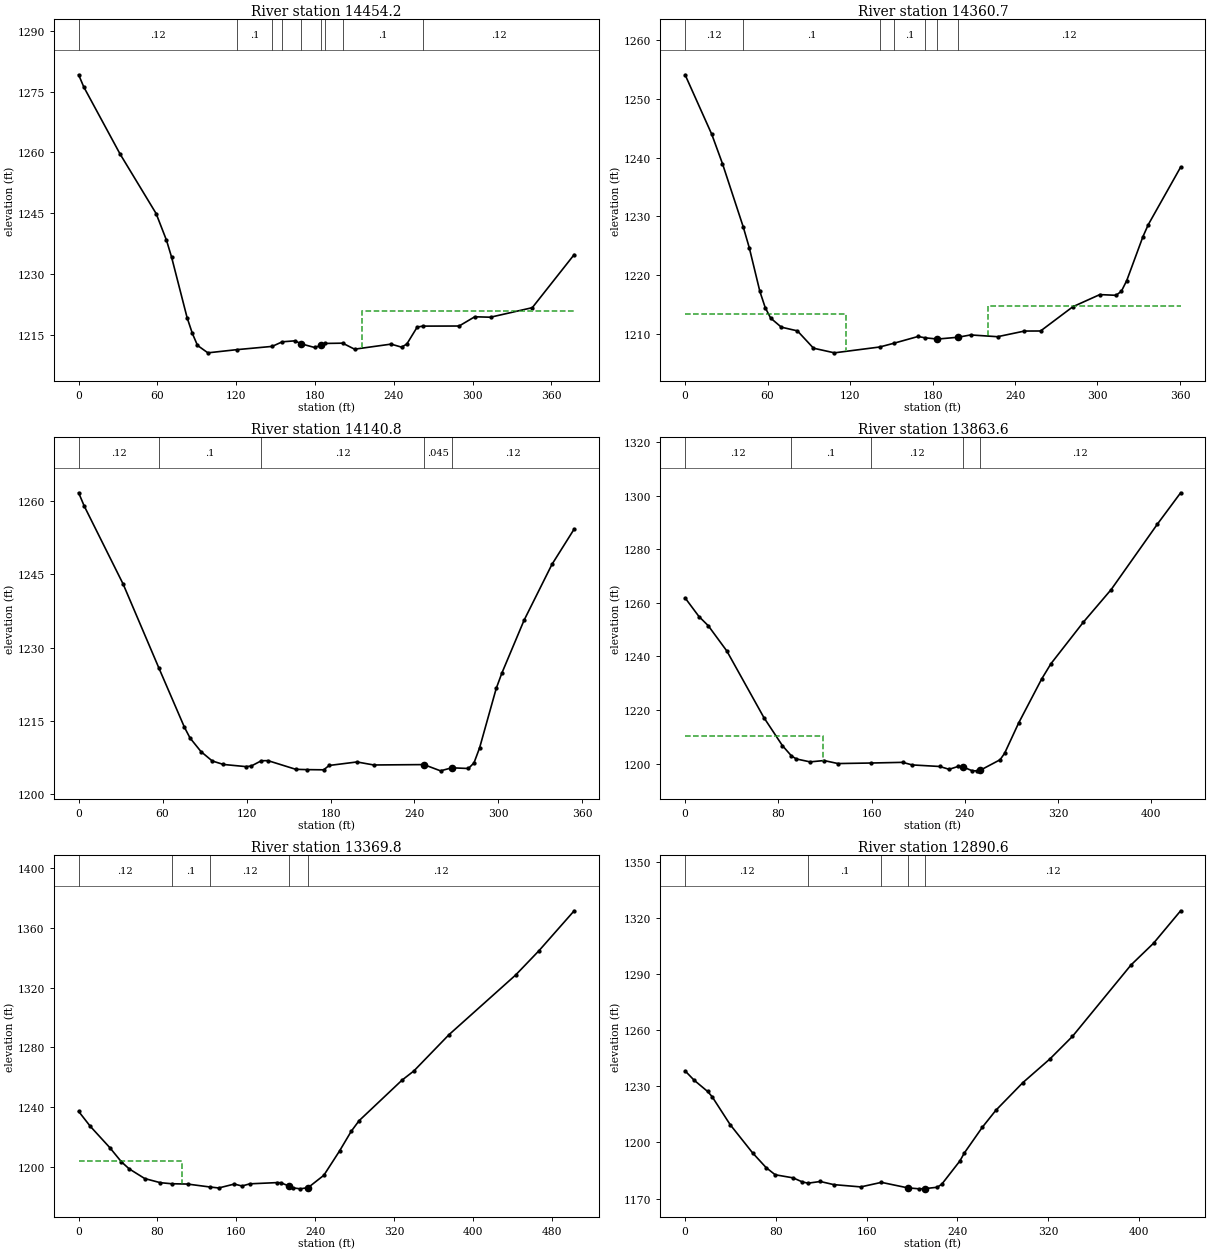
Type RM Length L Ch R = 1 ,14454.2 ,91,93.5,114.3
XS GIS Cut Line= 5
      1797157.79      361584.604     1797268.901      361610.646
     1797302.755       361590.68     1797334.005      361553.354
     1797504.144      361595.021
#Sta/Elev= 30
       0 1279.15     3.9 1276.16    31.5 1259.65      59 1244.95    66.9 1238.36
    70.8 1234.17    82.6 1219.27    86.6  1215.4    90.5 1212.45    98.4 1210.62
  120.331211.402  147.361212.209  155.031213.336   164.7 1213.58   169.4 1212.85
   179.6 1211.94   184.4 1212.46  187.931212.938  201.031213.004   210.1 1211.52
   237.9 1212.77   245.9 1212.02   249.9  1212.8   257.8 1216.98  262.221217.206
   289.7 1217.23   301.6 1219.51   313.6  1219.4   345.4 1221.75   377.3 1234.83
#Mann= 9 ,-1 , 0
       0     .12       0  120.33      .1       0  147.36     .12       0
  155.03      .1       0   169.4    .045       0   184.4      .1       0
  187.93     .12       0  201.03      .1       0  262.22     .12       0
#XS Ineff= 2 , 0
                          215.94         1220.83
Permanent Ineff=
       F       F
Bank Sta=169.4,184.4
XS Rating Curve= 0 ,0
Exp/Cntr=0.3,0.1

Type RM Length L Ch R = 1 ,14360.7 ,179.5,220,241.5
XS GIS Cut Line= 5
     1797149.109      361658.389     1797229.838      361705.264
     1797286.014      361681.481     1797326.193      361660.125
     1797480.055      361706.349
#Sta/Elev= 30
       0 1254.05    19.4 1243.94    27.2 1238.95   42.241228.256    46.7 1224.67
    54.4 1217.26    58.3  1214.5    62.2 1212.74      70 1211.19    81.7 1210.56
    93.4 1207.62   108.6 1206.83  141.581207.821  152.071208.471   169.5 1209.61
  174.481209.383   183.6 1209.17   198.6 1209.48   207.7 1209.87   227.3 1209.57
   246.9 1210.53   258.6 1210.54   282.1 1214.66   301.7 1216.72   313.5  1216.6
   317.4 1217.29   321.3 1219.11   333.1 1226.58     337 1228.62   360.5 1238.37
#Mann= 7 ,-1 , 0
       0     .12       0   42.24      .1       0  141.58     .12       0
  152.07      .1       0  174.48     .12       0   183.6    .045       0
   198.6     .12       0
#XS Ineff= 2 , 0
           116.9 1213.43  220.24         1214.71
Permanent Ineff=
       F       F
Bank Sta=183.6,198.6
XS Rating Curve= 0 ,0
Exp/Cntr=0.3,0.1

Type RM Length L Ch R = 1 ,14140.8 ,273.2,277.2,279.1
XS GIS Cut Line= 2
      1797098.83      361665.514     1797307.529      361951.574
#Sta/Elev= 30
       0  1261.7       4 1258.98    31.8    1243   57.431225.746    75.6 1213.67
    79.6 1211.47    87.5 1208.66    95.5 1206.76   103.4 1206.05   119.4 1205.61
   123.3 1205.72  130.551206.806   135.3 1206.83   155.2 1205.05   163.1 1204.99
   175.1 1204.95     179 1205.84   198.9 1206.56   210.9 1205.94   246.7 1206.02
   258.6 1204.74   266.6 1205.36   278.5 1205.22   282.5 1206.36   286.5 1209.43
   298.4 1221.62   302.4 1224.74   318.3 1235.59   338.2 1247.02   354.1 1254.27
#Mann= 5 ,-1 , 0
       0     .12       0   57.43      .1       0  130.55     .12       0
   246.7    .045       0   266.6     .12       0
Bank Sta=246.7,266.6
XS Rating Curve= 0 ,0
Exp/Cntr=0.3,0.1

Type RM Length L Ch R = 1 ,13863.6 ,497.4,493.8,490
XS GIS Cut Line= 2
     1796884.129      361751.105     1797097.259      362119.117
#Sta/Elev= 30
       0 1261.79    11.9 1254.85    19.9 1251.41    35.8    1242    67.6 1217.16
    83.5 1206.69   91.241202.865    95.4 1201.71   107.3 1200.61   119.2 1201.11
   131.2 1199.99   159.51200.188   186.8 1200.44   194.8 1199.48   218.6 1198.89
   226.6 1197.84   234.5 1198.94   238.2 1198.78   246.4  1197.3   250.4 1197.27
   253.2 1197.46   270.3  1201.4   274.2  1203.8   286.2 1215.06     306 1231.52
     314 1237.25   341.8 1252.74   365.7 1264.92   405.4 1289.36   425.3 1301.02
#Mann= 5 ,-1 , 0
       0     .12       0   91.24      .1       0   159.5     .12       0
   238.2    .045       0   253.2     .12       0
#XS Ineff= 2 , 0
          118.71 1210.17
Permanent Ineff=
       F       F
Bank Sta=238.2,253.2
XS Rating Curve= 0 ,0
Exp/Cntr=0.3,0.1

Type RM Length L Ch R = 1 ,13369.8 ,488.5,479.1,469
XS GIS Cut Line= 3
     1796449.472      361994.514     1796592.751      362162.958
     1796772.018      362380.526
#Sta/Elev= 30
       0 1237.32    11.8 1227.37    31.6 1213.14    43.4 1203.64    51.3 1198.94
    67.1 1192.46    82.9  1189.7   94.331188.999   110.6 1188.78  133.321186.814
   142.2 1186.17     158 1188.78   165.8 1187.49   173.8 1188.94   201.4 1189.75
   205.3 1189.66   213.6  1187.4   217.2 1186.26   225.1 1185.59     233 1186.44
   248.9 1194.64   264.8 1210.84   276.7 1224.03   284.7 1231.12   328.3 1258.21
   340.3 1264.33     376 1288.59   443.5 1328.34   467.3 1344.65     503  1371.3
#Mann= 5 ,-1 , 0
       0     .12       0   94.33      .1       0  133.32     .12       0
   213.6    .045       0     233     .12       0
#XS Ineff= 2 , 0
          105.14 1203.87
Permanent Ineff=
       F       F
Bank Sta=213.6,233
XS Rating Curve= 0 ,0
Exp/Cntr=0.3,0.1

Type RM Length L Ch R = 1 ,12890.6 ,565.4,549.1,532.5
XS GIS Cut Line= 2
     1796111.949      362413.219     1796510.936      362590.367
#Sta/Elev= 30
       0 1238.26     7.9 1233.31    19.8 1227.28    23.8 1224.49    39.7 1209.54
    59.5 1194.42    71.4 1186.56    79.4 1182.75    95.2 1181.09   103.2 1178.94
  108.34 1178.25   119.1 1179.16     131 1177.48   154.8 1176.26  172.971178.693
   196.1 1175.76   206.4 1175.23   211.1 1175.34   222.2 1176.08   226.2 1177.75
   242.1 1190.12     246 1194.36   261.9 1208.16   273.8  1217.2   297.6 1231.99
   321.5 1244.67   341.3  1256.7   392.9 1294.86   412.7 1306.44   436.6  1323.8
#Mann= 5 ,-1 , 0
       0     .12       0  108.34      .1       0  172.97     .12       0
   196.1    .045       0   211.1     .12       0
Bank Sta=196.1,211.1
XS Rating Curve= 0 ,0
Exp/Cntr=0.3,0.1

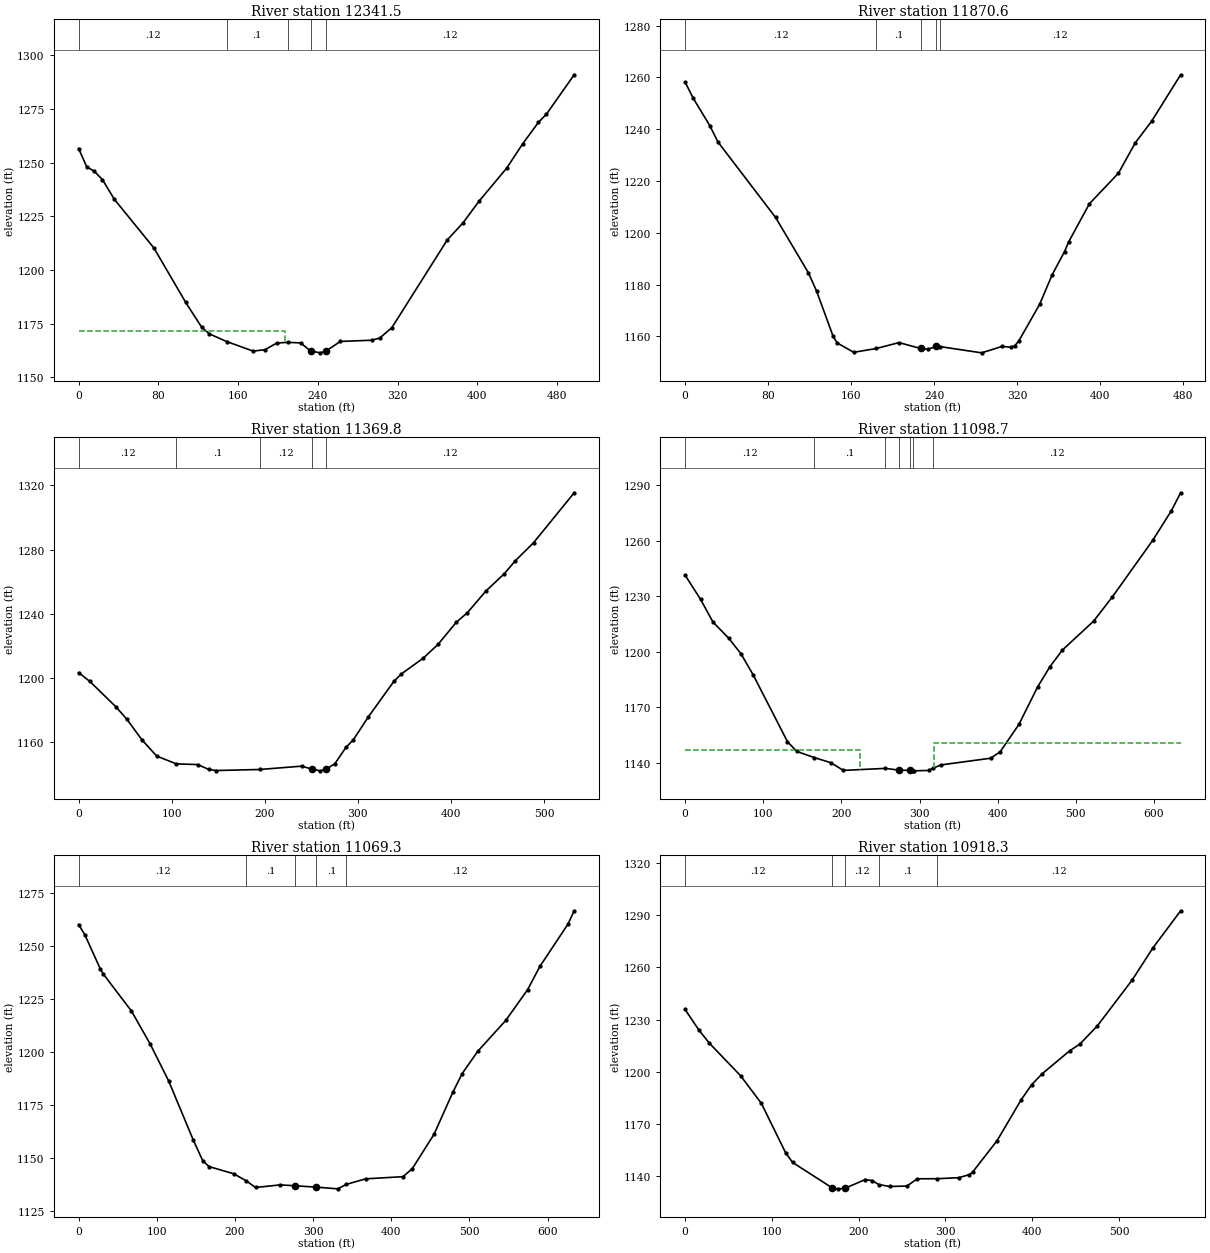
Type RM Length L Ch R = 1 ,12341.5 ,470.1,470.9,470.8
XS GIS Cut Line= 2
     1796039.032       363094.86     1796516.003      362954.863
#Sta/Elev= 30
       0 1256.52       8 1248.12    15.9 1245.84    23.9 1242.04    35.8 1232.91
    75.6 1210.18   107.4 1184.91   123.3 1173.42   131.2 1170.24  148.421166.705
     175 1162.24   186.9 1162.88   198.8 1165.99  209.981166.317   222.7 1166.05
   232.8 1162.25   242.6 1161.43   247.8 1162.15   262.5 1166.74   294.3 1167.31
   302.2 1168.37   314.2 1173.13   369.8 1213.99   385.7 1221.98   401.6 1231.97
   429.5 1247.45   445.4 1258.68   461.3 1268.72   469.3 1272.53   497.1 1290.84
#Mann= 5 ,-1 , 0
       0     .12       0  148.42      .1       0  209.98     .12       0
   232.8    .045       0   247.8     .12       0
#XS Ineff= 2 , 0
          207.46  1171.5
Permanent Ineff=
       F       F
Bank Sta=232.8,247.8
XS Rating Curve= 0 ,0
Exp/Cntr=0.3,0.1

Type RM Length L Ch R = 1 ,11870.6 ,498.4,500.8,502.6
XS GIS Cut Line= 3
     1796210.935        363523.2     1796435.718      363458.841
       1796669.2      363388.634
#Sta/Elev= 30
       0 1258.22     7.9 1251.93    23.8 1241.39    31.7 1235.07    87.2 1205.96
   118.9 1184.55   126.8 1177.44   142.7 1160.03   146.6  1157.5   162.5  1153.9
   184.41155.368   206.1 1157.64     227 1155.39   233.8 1155.07     242 1156.14
  245.891156.088   285.8 1153.69   305.8 1156.21   313.8 1155.82   317.8 1156.45
   321.8 1158.41   341.7  1172.4   353.7 1183.77   365.7 1192.77   369.7 1196.54
   389.7 1211.26   417.7 1223.06   433.7 1234.66   449.6 1243.09   477.6 1261.03
#Mann= 5 ,-1 , 0
       0     .12       0   184.4      .1       0     227    .045       0
     242      .1       0  245.89     .12       0
Bank Sta=227,242
XS Rating Curve= 0 ,0
Exp/Cntr=0.3,0.1

Type RM Length L Ch R = 1 ,11369.8 ,255,271.1,304.8
XS GIS Cut Line= 3
     1796314.246      363962.553     1796570.336      363920.198
     1796837.574      363865.378
#Sta/Elev= 30
       0 1203.46      12 1197.99    39.9 1182.28    51.9 1174.39    67.9 1161.71
    83.9 1151.54  104.921146.705   127.8 1146.26   139.8 1143.25   147.8 1142.55
  194.731143.204   239.6 1145.28   251.2 1143.34   259.6 1142.36   266.2  1143.4
   275.4 1146.89   287.2 1156.94   295.2 1161.73     311 1175.71   338.6 1197.94
   346.6 1202.59   370.3 1212.46   386.1    1221   405.8 1234.79   417.7 1240.73
   437.5 1254.17   457.2 1264.87   469.1 1272.98   488.9 1284.33   532.4  1315.3
#Mann= 5 ,-1 , 0
       0     .12       0  104.92      .1       0  194.73     .12       0
   251.2    .045       0   266.2     .12       0
Bank Sta=251.2,266.2
XS Rating Curve= 0 ,0
Exp/Cntr=0.3,0.1

Type RM Length L Ch R = 1 ,11098.7 ,19.2,29.4,29.2
XS GIS Cut Line= 4
     1796319.306      364238.918     1796571.042      364166.002
     1796589.271      364212.008     1796896.563      364113.918
#Sta/Elev= 30
       0  1241.4    19.8 1228.33    35.7 1216.08    55.6 1207.48    71.5 1198.97
    87.4 1187.37     131 1151.54     143 1146.27  165.131142.995   186.6 1140.18
   202.5 1136.05  256.261137.134   273.3 1136.22   288.3 1136.01   291.1 1135.88
   292.5 1135.81   311.6 1136.02  317.571137.295   327.5 1139.01   391.2 1142.63
   403.2 1146.11   427.1 1160.82     451 1181.01   466.9 1192.05   482.8 1200.99
   522.6 1216.53   546.5 1229.53   598.3 1260.14   622.2 1276.13   634.1 1285.85
#Mann= 7 ,-1 , 0
       0     .12       0  165.13      .1       0  256.26     .12       0
   273.3    .045       0   288.3     .12       0   291.1      .1       0
  317.57     .12       0
#XS Ineff= 2 , 0
          223.18 1146.79  318.15         1150.86
Permanent Ineff=
       F       F
Bank Sta=273.3,288.3
XS Rating Curve= 0 ,0
Exp/Cntr=0.3,0.1

Type RM Length L Ch R = 1 ,11069.3 ,185.2,151.1,110.6
XS GIS Cut Line= 4
     1796300.209      364258.883     1796551.945      364185.967
     1796570.174      364231.974     1796877.466      364133.883
#Sta/Elev= 30
       0 1260.16     7.9  1255.4    27.8 1239.19    31.8 1236.72    67.5 1219.42
    91.3 1203.98   115.2 1186.38   146.9 1158.32   158.8 1148.76   166.8 1145.97
   198.6 1142.56  214.641139.203   226.4  1136.1   258.1 1137.33   277.1  1136.9
     304 1136.27   331.5 1135.46   342.71137.589   367.3 1140.18   415.1  1141.2
   427.1 1145.05   454.9 1161.29   478.8 1181.01   490.8 1189.86   510.7 1200.36
   546.5 1214.91   574.4 1229.38   590.3 1240.46   626.2  1260.4   634.1 1266.68
#Mann= 5 ,-1 , 0
       0     .12       0  214.64      .1       0   277.1    .045       0
     304      .1       0   342.7     .12       0
Bank Sta=277.1,304
XS Rating Curve= 0 ,0
Exp/Cntr=0.3,0.1

Type RM Length L Ch R = 1 ,10918.3 ,317.6,320.2,322.7
XS GIS Cut Line= 2
     1796428.922      364431.644     1796929.495      364156.794
#Sta/Elev= 30
       0  1235.8      16  1223.9      28 1216.39    63.9 1197.68    87.9 1181.76
   115.8 1153.33   123.8 1147.76     169 1133.24   175.7 1132.52     184 1132.79
   207.7 1137.87   215.6 1137.26  223.141135.016   235.6 1133.87   255.6 1134.13
   267.6  1138.3  290.53 1138.35   315.5 1138.96   327.5 1140.68   331.5 1142.25
   359.4 1160.16   387.4 1183.86   399.4 1192.48   411.3 1198.71   443.3 1212.03
   455.3 1216.03   475.2 1226.43   515.2 1252.74   539.1 1271.25   571.1 1292.65
#Mann= 5 ,-1 , 0
       0     .12       0     169    .045       0     184     .12       0
  223.14      .1       0  290.53     .12       0
Bank Sta=169,184
XS Rating Curve= 0 ,0
Exp/Cntr=0.3,0.1