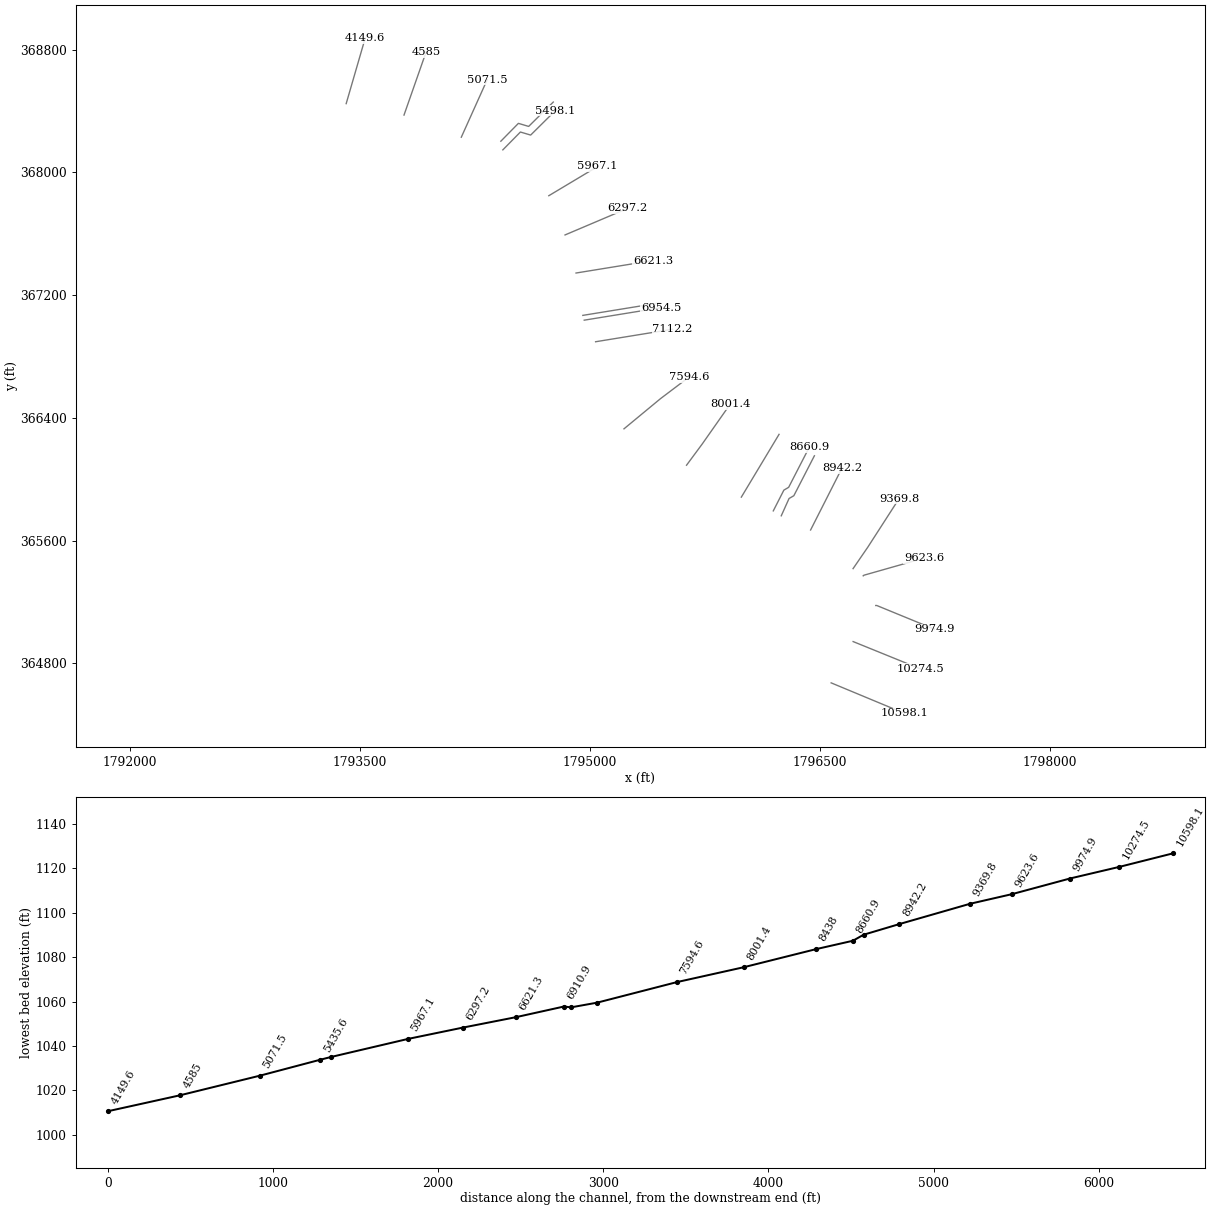
HEC-RAS study LOGANFK.prj: LOGANFK

--- LOGANFK.g01 (geometry) --- (continued)

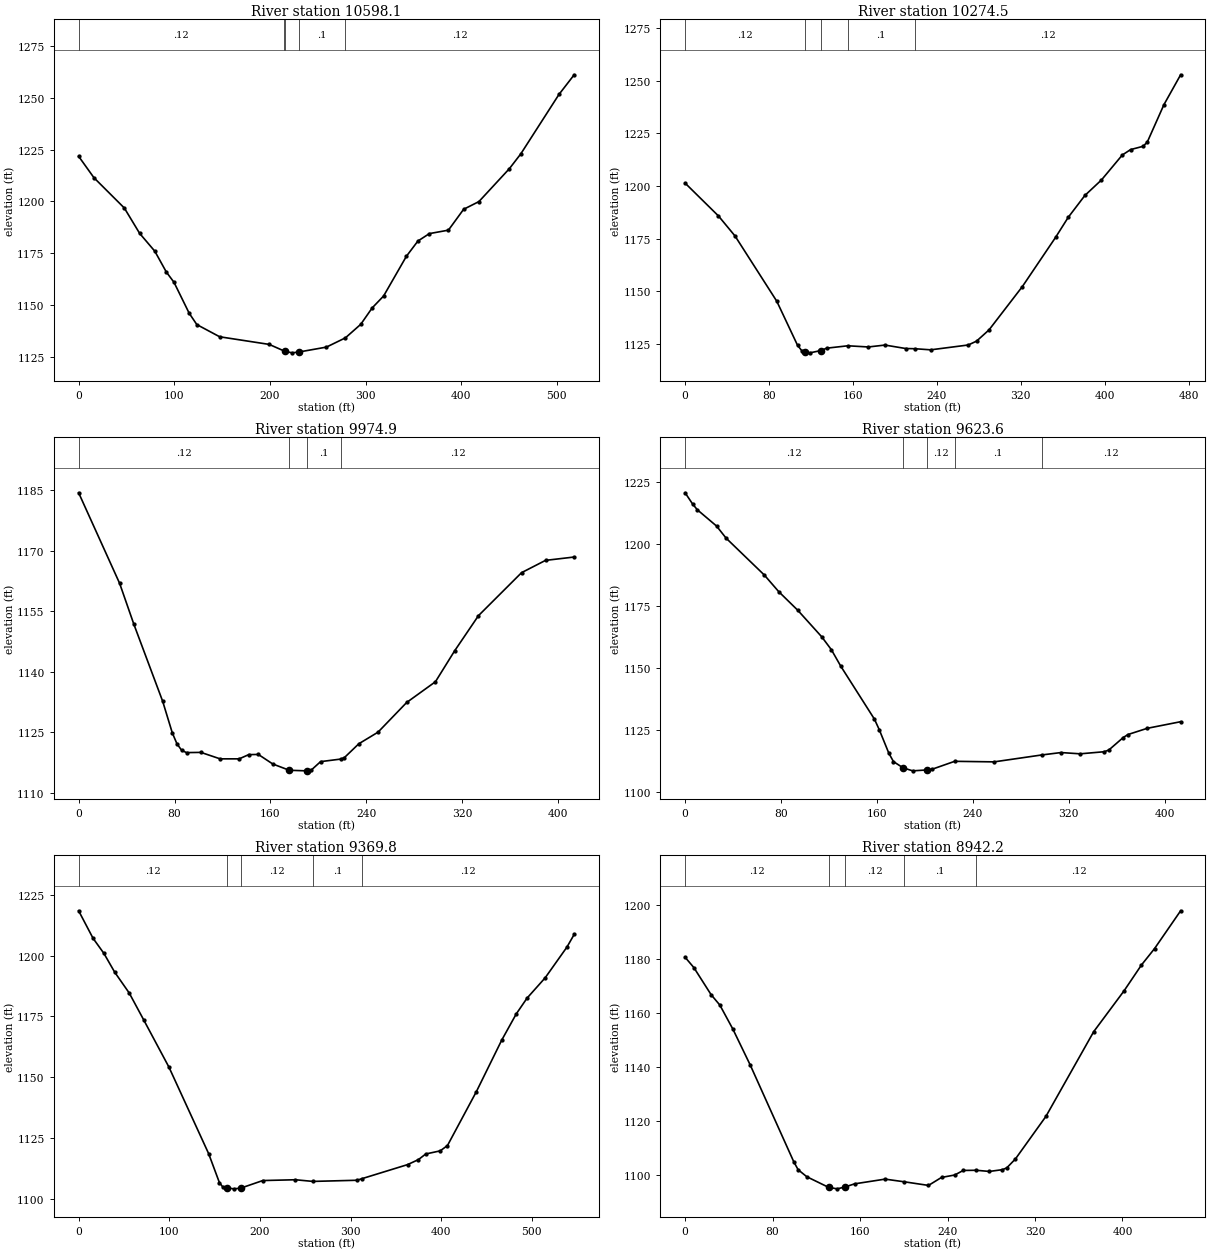
Type RM Length L Ch R = 1 ,10598.1 ,323.3,323.5,323.5
XS GIS Cut Line= 2
     1796573.664      364672.078     1797052.252      364473.229
#Sta/Elev= 30
       0 1221.86      16 1211.51    47.8 1196.84    63.8 1184.58    79.7 1175.93
    91.7 1165.89    99.7 1160.93   115.6 1145.95   123.6 1140.46   147.5 1134.56
   199.3 1130.87     2151127.664   215.3  1127.6   223.2 1126.79   230.3 1127.19
   259.1 1129.56  278.971134.036     295 1140.58     307 1148.54   318.9 1154.27
   342.8 1173.53   354.8 1180.88   366.8 1184.47   386.7 1186.14   402.6 1196.23
   418.6 1199.96   450.5 1215.91   462.4 1223.05   502.3 1251.79   518.2  1261.3
#Mann= 5 ,-1 , 0
       0     .12       0     215      .1       0   215.3    .045       0
   230.3      .1       0  278.97     .12       0
Bank Sta=215.3,230.3
XS Rating Curve= 0 ,0
Exp/Cntr=0.3,0.1

Type RM Length L Ch R = 1 ,10274.5 ,299.7,299.6,299.6
XS GIS Cut Line= 2
     1796717.006       364941.25     1797154.817      364763.638
#Sta/Elev= 30
       0 1201.34    31.8 1185.74    47.6 1176.23    87.4 1145.25   107.2 1124.32
   111.2 1121.76   114.4 1121.12   119.1 1120.72   129.4  1121.8     135 1122.94
   155.2 1124.07   174.7 1123.51   190.6 1124.41   210.4 1122.77  218.95 1122.68
   234.2 1122.15     270 1124.45   277.9 1126.28   289.8 1131.62   321.6 1152.21
   353.4 1175.67   365.3 1185.07   381.2 1195.47     397 1202.83   416.9  1214.7
   424.8 1217.26   436.7 1218.82   440.7 1220.83   456.6 1238.62   472.5 1252.79
#Mann= 5 ,-1 , 0
       0     .12       0   114.4    .045       0   129.4     .12       0
   155.2      .1       0  218.95     .12       0
Bank Sta=114.4,129.4
XS Rating Curve= 0 ,0
Exp/Cntr=0.3,0.1

Type RM Length L Ch R = 1 ,9974.9  ,334.3,351.3,367.7
XS GIS Cut Line= 3
     1796864.653      365176.297     1796870.868      365176.522
     1797247.513      365022.037
#Sta/Elev= 30
       0 1184.37    34.2 1161.92    46.1 1151.76    70.1  1132.7    78.1  1124.9
      82 1122.17      86 1120.53      90 1119.99     102 1120.04     118 1118.44
   133.9 1118.44   141.9 1119.49   149.9 1119.53   161.9 1117.17   175.7 1115.61
   189.8 1115.47   190.7  1115.5   193.8  1115.6   201.8 1117.75  218.841118.393
   221.7 1118.76   233.7 1122.18   249.7 1125.05   273.6 1132.41   297.6 1137.55
   313.5 1145.16   333.5 1153.93   369.4 1164.57   389.4 1167.62   413.3 1168.45
#Mann= 4 ,-1 , 0
       0     .12       0   175.7    .045       0   190.7      .1       0
  218.84     .12       0
Bank Sta=175.7,190.7
XS Rating Curve= 0 ,0
Exp/Cntr=0.3,0.1

Type RM Length L Ch R = 1 ,9623.6  ,238.2,253.8,269.7
XS GIS Cut Line= 3
     1796782.694      365369.769     1796787.444      365373.785
     1797179.067       365484.95
#Sta/Elev= 30
       0 1220.65     6.2 1216.17    10.2 1213.79    26.2 1207.24    34.2 1202.34
    66.1 1187.44    78.1 1180.74      94 1173.22     114 1162.49     122 1157.31
   129.9 1150.61   157.9 1129.29   161.9 1125.08   169.9 1115.56   173.8 1112.14
   181.8 1109.64   189.8 1108.42   201.8 1108.78   205.8 1109.03  224.851112.265
   257.7 1112.04  297.441114.828   313.5  1115.8   329.5 1115.29   349.5 1116.13
   353.4 1116.82   365.4 1121.86   369.4 1123.08   385.4 1125.58   413.3 1128.25
#Mann= 5 ,-1 , 0
       0     .12       0   181.8    .045       0   201.8     .12       0
  224.85      .1       0  297.44     .12       0
Bank Sta=181.8,201.8
XS Rating Curve= 0 ,0
Exp/Cntr=0.3,0.1

Type RM Length L Ch R = 1 ,9369.8  ,424.3,427.6,430.1
XS GIS Cut Line= 3
      1796716.65      365416.683     1796813.571      365557.871
     1797017.117      365873.456
#Sta/Elev= 30
       0 1218.49    15.9 1207.18    27.9 1200.95    39.8 1193.22    55.8 1184.67
    71.7 1173.66    99.6  1154.2   143.4 1118.61   155.3 1106.68   159.3 1104.73
   163.8 1104.48   171.2 1104.08   178.8 1104.36   203.2 1107.49   239.2 1107.82
  258.471107.137   307.1 1107.61  312.971108.304     363 1114.05     375 1116.12
     383 1118.42     399 1119.71     407  1121.9   438.9 1144.09   466.9  1165.3
   482.9 1176.06   494.8 1182.55   514.8 1190.91   538.8 1203.54   546.8 1208.76
#Mann= 5 ,-1 , 0
       0     .12       0   163.8    .045       0   178.8     .12       0
  258.47      .1       0  312.97     .12       0
Bank Sta=163.8,178.8
XS Rating Curve= 0 ,0
Exp/Cntr=0.3,0.1

Type RM Length L Ch R = 1 ,8942.2  ,224.2,216.5,204.1
XS GIS Cut Line= 2
     1796439.564       365668.58     1796644.593      366072.737
#Sta/Elev= 30
       0 1180.79       8 1176.97    23.8 1166.91    31.8 1163.05    43.7 1154.15
    59.6 1140.82    99.4 1104.96   103.4 1102.02   111.3 1099.43   131.3 1095.48
   139.1 1094.94   146.3 1095.64     155 1096.79   182.9 1098.54  200.071097.572
   222.6 1096.21   234.5 1099.17   246.5 1100.06   254.4 1101.76  266.311101.821
   278.3 1101.39   290.2 1102.05   294.2 1102.72   302.1 1106.02     330  1121.8
   373.7 1153.21   401.5 1168.37   417.4 1177.94   429.3 1183.98   453.2 1198.02
#Mann= 5 ,-1 , 0
       0     .12       0   131.3    .045       0   146.3     .12       0
  200.07      .1       0  266.31     .12       0
Bank Sta=131.3,146.3
XS Rating Curve= 0 ,0
Exp/Cntr=0.3,0.1

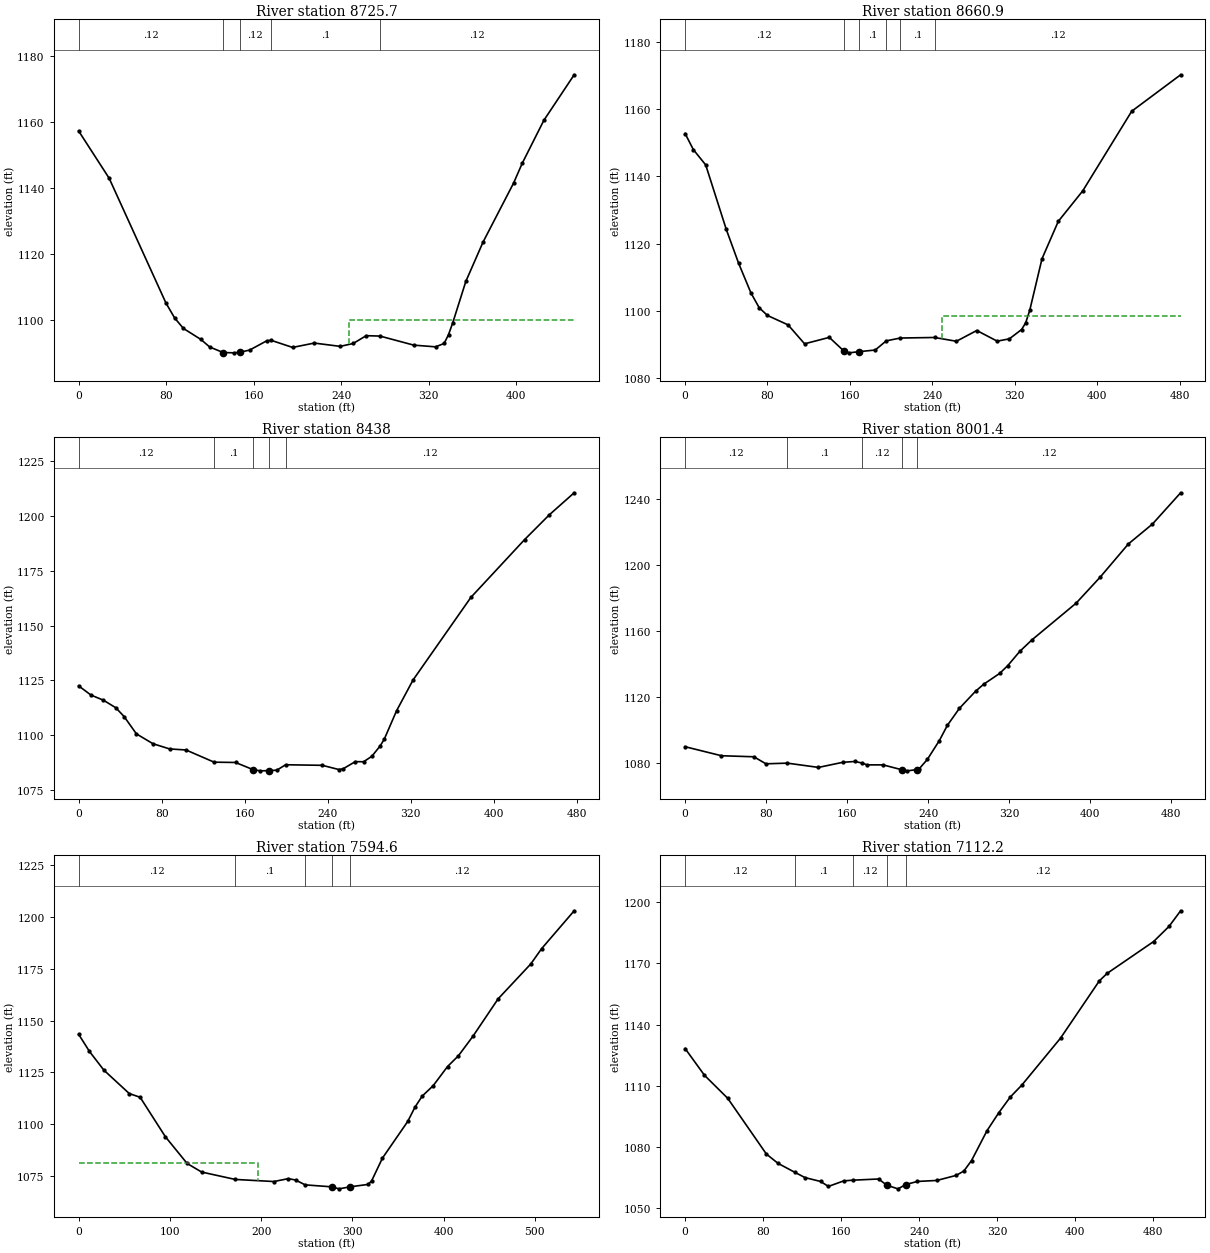
Type RM Length L Ch R = 1 ,8725.7  ,62,64.8,64.1
XS GIS Cut Line= 4
     1796248.158      365761.028     1796298.994      365873.771
     1796330.244         365892.     1796464.358      366152.416
#Sta/Elev= 30
       0 1157.36    27.9 1143.03    79.8 1105.22    87.8 1100.66    95.8 1097.52
   111.7  1094.2   119.7 1091.92     132 1090.24   141.8 1090.14     147 1090.31
   156.2 1090.97   171.7 1093.75  175.691093.959   195.5 1091.78   215.3  1093.1
     239  1092.1   250.9 1092.98   262.8 1095.34  275.361095.217   306.3 1092.47
   326.1 1091.96     334 1092.98     338 1095.68   341.9 1099.29   353.8 1111.78
   369.6 1123.74   397.4 1141.54   405.3 1147.54   425.1 1160.58   452.8 1174.38
#Mann= 5 ,-1 , 0
       0     .12       0     132    .045       0     147     .12       0
  175.69      .1       0  275.36     .12       0
#XS Ineff= 2 , 0
                          247.03            1100
Permanent Ineff=
       F       F
Bank Sta=132,147
XS Rating Curve= 0 ,0
Exp/Cntr=0.3,0.1

Type RM Length L Ch R = 1 ,8660.9  ,219.7,222.9,234.3
XS GIS Cut Line= 4
     1796196.129      365793.041     1796265.139      365928.458
     1796296.389      365946.687     1796430.504      366207.104
#Sta/Elev= 30
       0 1152.81       8 1148.01      20 1143.45      40  1124.2      52 1114.09
      64 1105.23      72 1100.84      80 1098.56     100 1095.75     116 1090.11
     140 1092.03   153.8 1088.06   159.2 1087.42   168.8 1087.77   184.6 1088.26
  195.321090.997  208.941091.836  242.161091.997   263.4 1090.87   283.2 1094.08
     303  1090.9   314.8 1091.59   326.7 1094.37   330.7  1096.4   334.6  1100.1
   346.5 1115.47   362.3 1126.61   386.1 1135.73   433.6 1159.45   481.1 1170.32
#Mann= 6 ,-1 , 0
       0     .12       0   153.8    .045       0   168.8      .1       0
  195.32     .12       0  208.94      .1       0  242.16     .12       0
#XS Ineff= 2 , 0
                          249.58         1098.45
Permanent Ineff=
       F       F
Bank Sta=153.8,168.8
XS Rating Curve= 0 ,0
Exp/Cntr=0.3,0.1

Type RM Length L Ch R = 1 ,8438    ,438.2,436.6,434.4
XS GIS Cut Line= 2
     1795987.705      365882.819     1796233.772      366292.058
#Sta/Elev= 30
       0 1122.45    11.9 1118.24    23.9  1115.9    35.8 1112.46    43.8 1108.45
    55.7 1100.52    71.6 1096.04    87.6 1093.66   103.5 1093.17  130.551087.606
   151.2 1087.47   168.2 1084.18   175.1 1083.65   183.2 1083.74     191 1083.96
  199.471086.428   234.8 1086.17   250.7 1084.25   254.7 1084.54   266.6 1087.85
   274.6  1087.8   282.5 1090.28   290.5 1094.98   294.5 1098.09   306.4 1111.12
   322.3 1125.17     378 1162.85   429.8 1189.26   453.6 1200.56   477.5  1210.6
#Mann= 5 ,-1 , 0
       0     .12       0  130.55      .1       0   168.2    .045       0
   183.2      .1       0  199.47     .12       0
Bank Sta=168.2,183.2
XS Rating Curve= 0 ,0
Exp/Cntr=0.3,0.1

Type RM Length L Ch R = 1 ,8001.4  ,412.8,406.8,400.5
XS GIS Cut Line= 3
     1795630.123      366090.739     1795732.224      366228.715
     1795914.909      366488.617
#Sta/Elev= 30
       0 1090.14    35.9 1084.67    67.9 1084.04    79.8 1079.78     1011080.182
   131.7  1077.6   155.7 1080.69   167.6 1081.19  174.441080.309   179.6 1079.14
   195.5 1079.13   214.3 1076.12   219.3 1075.52   229.3 1076.28   231.2 1076.78
   239.2 1082.45   251.1  1093.9     259 1103.11   270.9 1113.42   286.8 1123.75
   294.8 1127.98   310.6 1134.55   318.6 1139.27   330.5 1147.92   342.4 1154.84
   386.1 1177.11   409.9 1192.92   437.7    1213   461.5 1225.07   489.3    1244
#Mann= 5 ,-1 , 0
       0     .12       0     101      .1       0  174.44     .12       0
   214.3    .045       0   229.3     .12       0
Bank Sta=214.3,229.3
XS Rating Curve= 0 ,0
Exp/Cntr=0.3,0.1

Type RM Length L Ch R = 1 ,7594.6  ,494.4,482.4,470.3
XS GIS Cut Line= 3
     1795222.145      366327.962     1795460.529      366524.809
     1795647.273      366665.764
#Sta/Elev= 30
       0 1143.42    11.9 1135.13    27.7 1126.09    55.5  1114.8    67.4    1113
    95.1 1093.93   118.9 1081.04   134.8 1076.89  171.671073.318     214 1072.31
   229.9 1073.72   237.8 1073.03  248.281070.698   277.3 1069.75   285.4 1068.78
   297.3 1069.74   317.1 1070.91     321 1072.53     333 1083.64   360.7 1101.34
   368.6 1108.22   376.6 1113.61   388.5 1118.56   404.3 1127.85   416.2 1133.03
   432.1 1142.44   459.8 1160.57   495.5 1177.37   507.4 1184.78   543.1 1203.08
#Mann= 5 ,-1 , 0
       0     .12       0  171.67      .1       0  248.28     .12       0
   277.3    .045       0   297.3     .12       0
#XS Ineff= 2 , 0
          196.72 1081.14
Permanent Ineff=
       F       F
Bank Sta=277.3,297.3
XS Rating Curve= 0 ,0
Exp/Cntr=0.3,0.1

Type RM Length L Ch R = 1 ,7112.2  ,167.8,157.7,155.9
XS GIS Cut Line= 2
     1795036.928      366895.603     1795538.715      366977.155
#Sta/Elev= 30
       0 1128.32    19.9 1115.19    43.7 1103.93    83.4 1076.59    95.3 1072.03
   112.31067.699   123.1 1065.03     139 1063.15     147 1060.71   162.8 1063.44
  172.151063.773   198.6 1064.36   206.9 1061.31   218.4 1059.53   226.4 1061.64
   238.3 1063.15   258.2 1063.64     278 1066.11     286 1068.25   293.9 1073.42
   309.8 1088.08   321.7 1096.75   333.6 1104.52   345.5  1110.4   385.2 1133.43
     425 1161.49   432.9 1165.12   480.6 1180.73   496.5 1188.19   508.4 1195.84
#Mann= 5 ,-1 , 0
       0     .12       0   112.3      .1       0  172.15     .12       0
   206.9    .045       0   226.4     .12       0
Bank Sta=206.9,226.4
XS Rating Curve= 0 ,0
Exp/Cntr=0.3,0.1

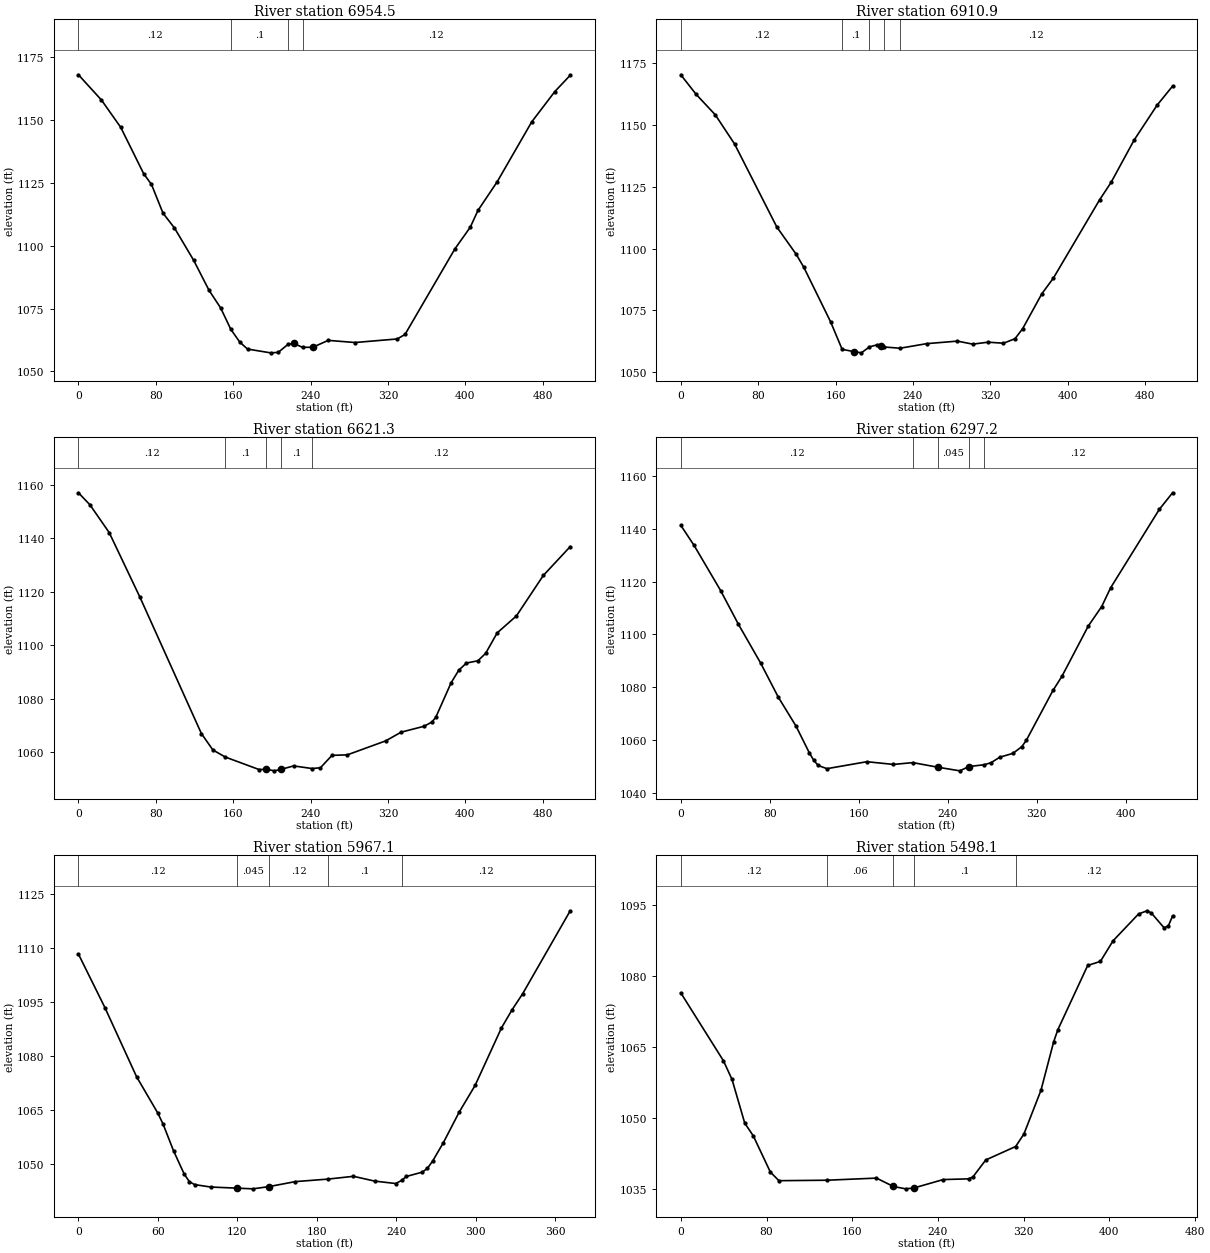
Type RM Length L Ch R = 1 ,6954.5  ,34,43.6,44.7
XS GIS Cut Line= 2
     1794962.709      367036.228     1795464.496       367117.78
#Sta/Elev= 30
       0  1168.1    23.8 1158.04    43.7 1147.19    67.5 1128.68    75.5 1124.46
    87.4 1113.03    99.3 1107.11   119.2  1094.2     135 1082.31     147  1075.3
  157.571066.744   166.8 1061.69   174.8 1058.92   198.6 1057.42   206.5  1057.6
   216.7 1060.81   222.4 1061.15   231.7 1059.62   242.3 1059.64   258.2 1062.38
     286 1061.53   329.6 1062.95   337.6 1064.74   389.2 1098.82   405.1 1107.44
     413 1114.09   432.9 1125.51   468.6 1149.35   492.5 1161.43   508.4 1167.91
#Mann= 4 ,-1 , 0
       0     .12       0  157.57      .1       0   216.7    .045       0
   231.7     .12       0
Bank Sta=222.4,242.3
XS Rating Curve= 0 ,0
Exp/Cntr=0.3,0.1

Type RM Length L Ch R = 1 ,6910.9  ,289.3,289.6,289.7
XS GIS Cut Line= 2
     1794953.594      367067.478     1795455.382       367149.03
#Sta/Elev= 30
       0 1170.43    15.9  1162.5    35.7  1154.2    55.6 1142.41    99.3 1108.75
   119.2 1097.78   127.1 1092.52   154.9 1070.34  166.811059.199   178.7 1058.29
   186.7 1057.78   195.1  1060.2   202.6 1060.98   206.5 1060.44   210.1 1060.16
  226.661059.645   254.2  1061.5     286 1062.53   301.8  1061.3   317.7  1062.1
   333.6 1061.67   345.5 1063.49   353.5 1067.61   373.3 1081.73   385.2 1088.06
   432.9 1119.72   444.8 1126.79   468.6 1143.94   492.5 1158.17   508.4 1165.81
#Mann= 5 ,-1 , 0
       0     .12       0  166.81      .1       0   195.1    .045       0
   210.1      .1       0  226.66     .12       0
Bank Sta=178.7,206.5
XS Rating Curve= 0 ,0
Exp/Cntr=0.3,0.1

Type RM Length L Ch R = 1 ,6621.3  ,318.5,324.1,329.8
XS GIS Cut Line= 2
     1794909.323      367343.519     1795411.111      367425.072
#Sta/Elev= 30
       0 1156.94    11.9 1152.44    31.8 1142.06    63.6 1117.89   127.1 1066.94
     139  1060.8  151.821058.154   186.7 1053.49   194.4 1053.58   202.6    1053
   209.4 1053.54   222.4 1054.84  241.591053.863   250.2 1054.16   262.1 1058.78
     278 1058.98   317.7 1064.21   333.6 1067.46   357.4 1069.67   365.4 1071.25
   369.4    1073   385.2 1085.87   393.2 1090.63   401.1 1093.29     413 1094.14
     421 1096.95   432.9 1104.57   452.8 1110.92   480.6 1126.04   508.4 1136.82
#Mann= 5 ,-1 , 0
       0     .12       0  151.82      .1       0   194.4    .045       0
   209.4      .1       0  241.59     .12       0
Bank Sta=194.4,209.4
XS Rating Curve= 0 ,0
Exp/Cntr=0.3,0.1

Type RM Length L Ch R = 1 ,6297.2  ,330.3,330.1,328.7
XS GIS Cut Line= 2
     1794837.568      367591.765     1795244.598      367764.388
#Sta/Elev= 30
       0 1141.32      12 1133.67    35.8  1116.6    51.8 1103.82    71.7 1089.18
    87.6 1076.24   103.6 1065.21   115.5 1055.14   119.5 1052.27   123.5  1050.3
   131.4 1049.08   167.3 1051.72   191.2 1050.69  208.641051.376     231 1049.64
   250.9 1048.26   258.9 1049.88  272.811050.571   278.8 1051.32   286.8 1053.42
   298.7  1054.9   306.7 1057.47   310.7 1059.88   334.6 1078.73   342.6 1084.04
   366.4 1103.18   378.4 1110.52   386.4 1117.61   430.2 1147.35   442.1 1153.64
#Mann= 5 ,-1 , 0
       0     .12       0  208.64      .1       0     231    .045       0
   258.9      .1       0  272.81     .12       0
Bank Sta=231,258.9
XS Rating Curve= 0 ,0
Exp/Cntr=0.3,0.1

Type RM Length L Ch R = 1 ,5967.1  ,489.1,469,453.6
XS GIS Cut Line= 2
      1794731.61      367847.433     1795050.255      368037.902
#Sta/Elev= 30
       0 1108.22      20 1093.38    43.9 1074.23    59.9 1064.18    63.9 1061.11
    71.8 1053.71    79.8  1047.3    83.8 1045.14    87.8 1044.36    99.8 1043.69
   119.8 1043.38   131.7 1043.19   143.8 1043.81   163.7 1045.19  188.451045.892
   207.6 1046.66   223.5 1045.34   239.5 1044.66     2441045.535   247.5 1046.62
   259.5 1047.81   263.4 1048.87   267.4 1050.91   275.4 1055.95   287.4 1064.45
   299.4 1071.84   319.3 1087.77   327.3 1092.79   335.3 1097.24   371.2 1120.22
#Mann= 5 ,-1 , 0
       0     .12       0   119.8    .045       0   143.8     .12       0
  188.45      .1       0     244     .12       0
Bank Sta=119.8,143.8
XS Rating Curve= 0 ,0
Exp/Cntr=0.3,0.1

Type RM Length L Ch R = 1 ,5498.1  ,60.4,62.5,61
XS GIS Cut Line= 4
     1794431.806       368146.34     1794546.389      368262.659
      1794613.23      368242.694      1794773.82      368401.548
#Sta/Elev= 30
       0 1076.41    39.8 1062.06    47.8 1058.13    59.7 1048.88    67.7 1046.18
    83.6 1038.54    91.6 1036.72  136.431036.821   182.6 1037.27   198.4  1035.5
   209.8    1035   217.5 1035.18   244.9 1036.96   268.7 1037.11   272.7 1037.54
   284.6  1041.1  312.481043.945   320.2 1046.58   336.1 1055.81     348  1066.1
   351.9 1068.64   379.7 1082.19   391.6 1083.06   403.4 1087.41   427.2 1093.08
   435.1 1093.75   439.1 1093.28     451 1090.15     455 1090.57   458.9 1092.64
#Mann= 5 ,-1 , 0
       0     .12       0  136.43     .06       0   198.4    .045       0
   217.5      .1       0  312.48     .12       0
Bank Sta=198.4,217.5
XS Rating Curve= 0 ,0
Exp/Cntr=0.3,0.1

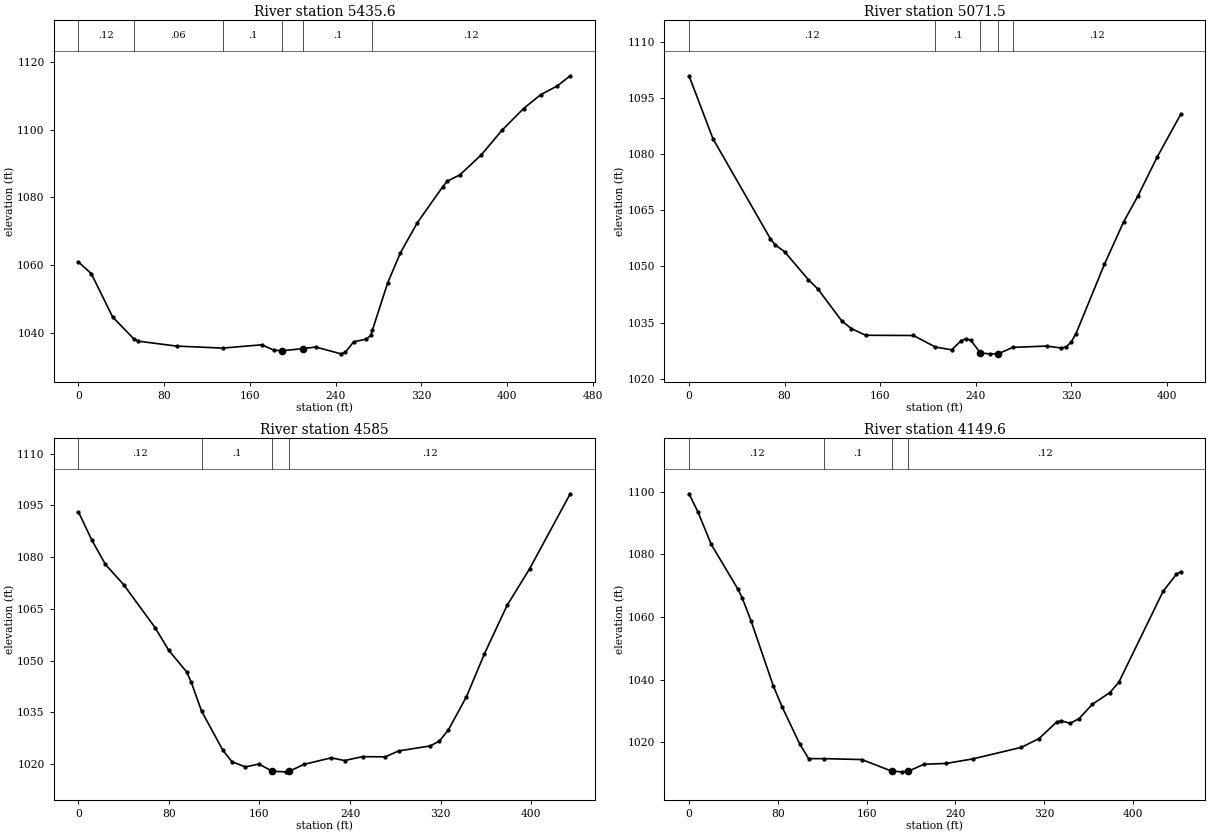
Type RM Length L Ch R = 1 ,5435.6  ,329.2,364.1,398.8
XS GIS Cut Line= 4
     1794418.785      368202.764     1794533.369      368319.083
     1794600.209      368299.118     1794760.799      368457.972
#Sta/Elev= 30
       0 1060.95      12 1057.48    31.9  1044.7   51.561038.269    55.8 1037.55
    91.6  1036.1  134.481035.505     171 1036.48   182.6 1034.87   190.3 1034.73
   209.8 1035.36   221.4 1035.83   244.9 1033.81   248.9 1034.21   256.8 1037.36
   268.7 1038.16   272.7 1039.25  274.251040.764   288.5 1054.71   300.4 1063.62
   316.3 1072.57     340 1083.18     344 1084.77   355.9 1086.66   375.7  1092.5
   395.5 1099.93   415.3 1106.24   431.2 1110.31     447 1112.96   458.9 1115.93
#Mann= 6 ,-1 , 0
       0     .12       0   51.56     .06       0  134.48      .1       0
   190.3    .045       0   209.8      .1       0  274.25     .12       0
Bank Sta=190.3,209.8
XS Rating Curve= 0 ,0
Exp/Cntr=0.3,0.1

Type RM Length L Ch R = 1 ,5071.5  ,484.2,486.5,487.9
XS GIS Cut Line= 2
     1794160.795      368228.715     1794329.936      368604.141
#Sta/Elev= 30
       0 1100.94      20 1084.14      68 1057.46      72  1055.8      80 1053.93
    99.9 1046.48   107.9 1043.97   127.9 1035.43   135.9  1033.4   147.9 1031.61
   187.9 1031.55   206.21028.478   219.9 1027.72   227.9 1030.17   231.9 1030.69
   235.9 1030.29     244 1026.86   251.9 1026.65     259 1026.67  270.991028.377
   299.8 1028.73   311.8  1028.2   315.8 1028.52   319.8 1029.71   323.8 1031.88
   347.8 1050.56   363.8 1061.84   375.8 1068.78   391.8 1079.11   411.8  1090.7
#Mann= 5 ,-1 , 0
       0     .12       0   206.2      .1       0     244    .045       0
     259      .1       0  270.99     .12       0
Bank Sta=244,259
XS Rating Curve= 0 ,0
Exp/Cntr=0.3,0.1

Type RM Length L Ch R = 1 ,4585    ,433.9,435.4,436.7
XS GIS Cut Line= 2
        1793787.      368373.109     1793930.779      368783.202
#Sta/Elev= 30
       0 1093.11      12 1084.84    23.9 1077.87    39.9 1072.04    67.8 1059.54
    79.7 1053.04    95.7  1046.7    99.7 1043.72  108.821035.356   127.6 1024.04
   135.6 1020.71   147.5 1019.18   159.5 1020.02   171.4 1017.91   183.4 1017.76
   186.4 1017.94   199.3 1019.92   223.3 1021.82   235.2 1021.04   251.2 1022.17
   271.1  1022.1   283.1 1023.83     311 1025.28     319 1026.69   326.9 1029.91
   342.9 1039.54   358.8 1051.99   378.8 1066.01   398.7 1076.62   434.6 1098.37
#Mann= 4 ,-1 , 0
       0     .12       0  108.82      .1       0   171.4    .045       0
   186.4     .12       0
Bank Sta=171.4,186.4
XS Rating Curve= 0 ,0
Exp/Cntr=0.3,0.1

Type RM Length L Ch R = 1 ,4149.6  ,531,532,533.2
XS GIS Cut Line= 2
     1793409.764      368447.665     1793533.472      368873.273
#Sta/Elev= 30
       0 1099.36       8 1093.57      20  1083.2    43.9 1069.01    47.9 1066.13
    55.9 1058.77    75.9 1038.08    83.8 1031.39    99.8 1019.45   107.8 1014.82
  121.591014.809   155.7 1014.52   182.7 1010.81   191.7  1010.6   197.7  1010.8
   211.6 1013.01   231.6 1013.28   255.6 1014.72   299.5 1018.42   315.4 1021.22
   331.4 1026.54   335.4 1026.88   343.4  1026.1   351.4 1027.54   363.4 1032.14
   379.3 1035.92   387.3 1039.17   427.2  1068.2   439.2 1073.69   443.2  1074.5
#Mann= 4 ,-1 , 0
       0     .12       0  121.59      .1       0   182.7    .045       0
   197.7     .12       0
Bank Sta=182.7,197.7
XS Rating Curve= 0 ,0
Exp/Cntr=0.3,0.1