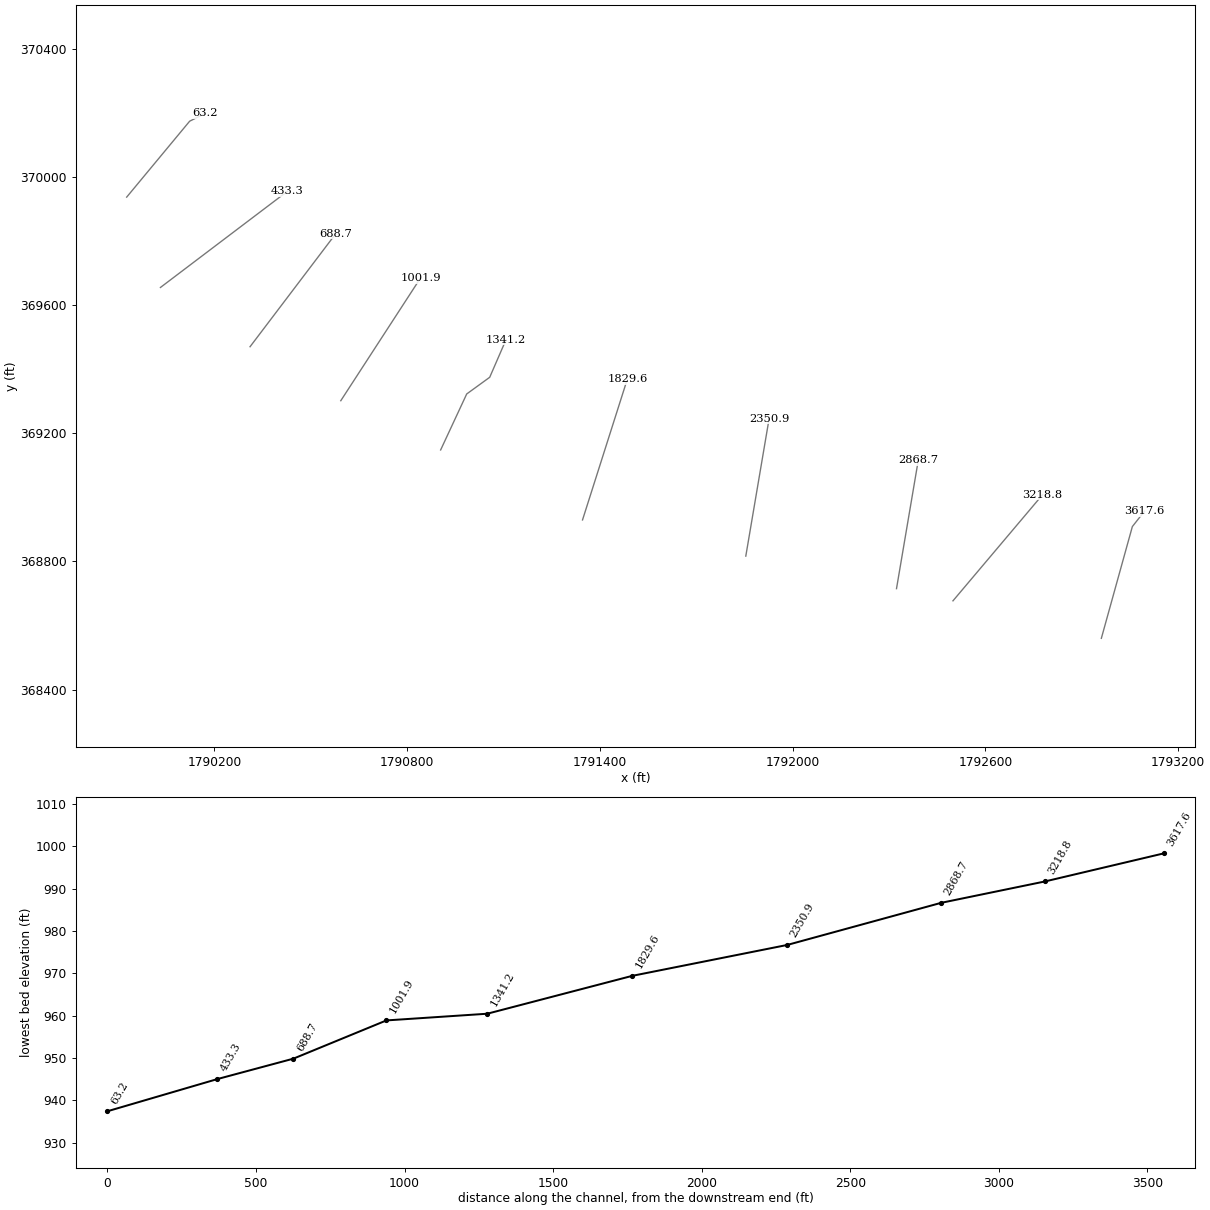
HEC-RAS study LOGANFK.prj: LOGANFK

--- LOGANFK.g01 (geometry) --- (continued)

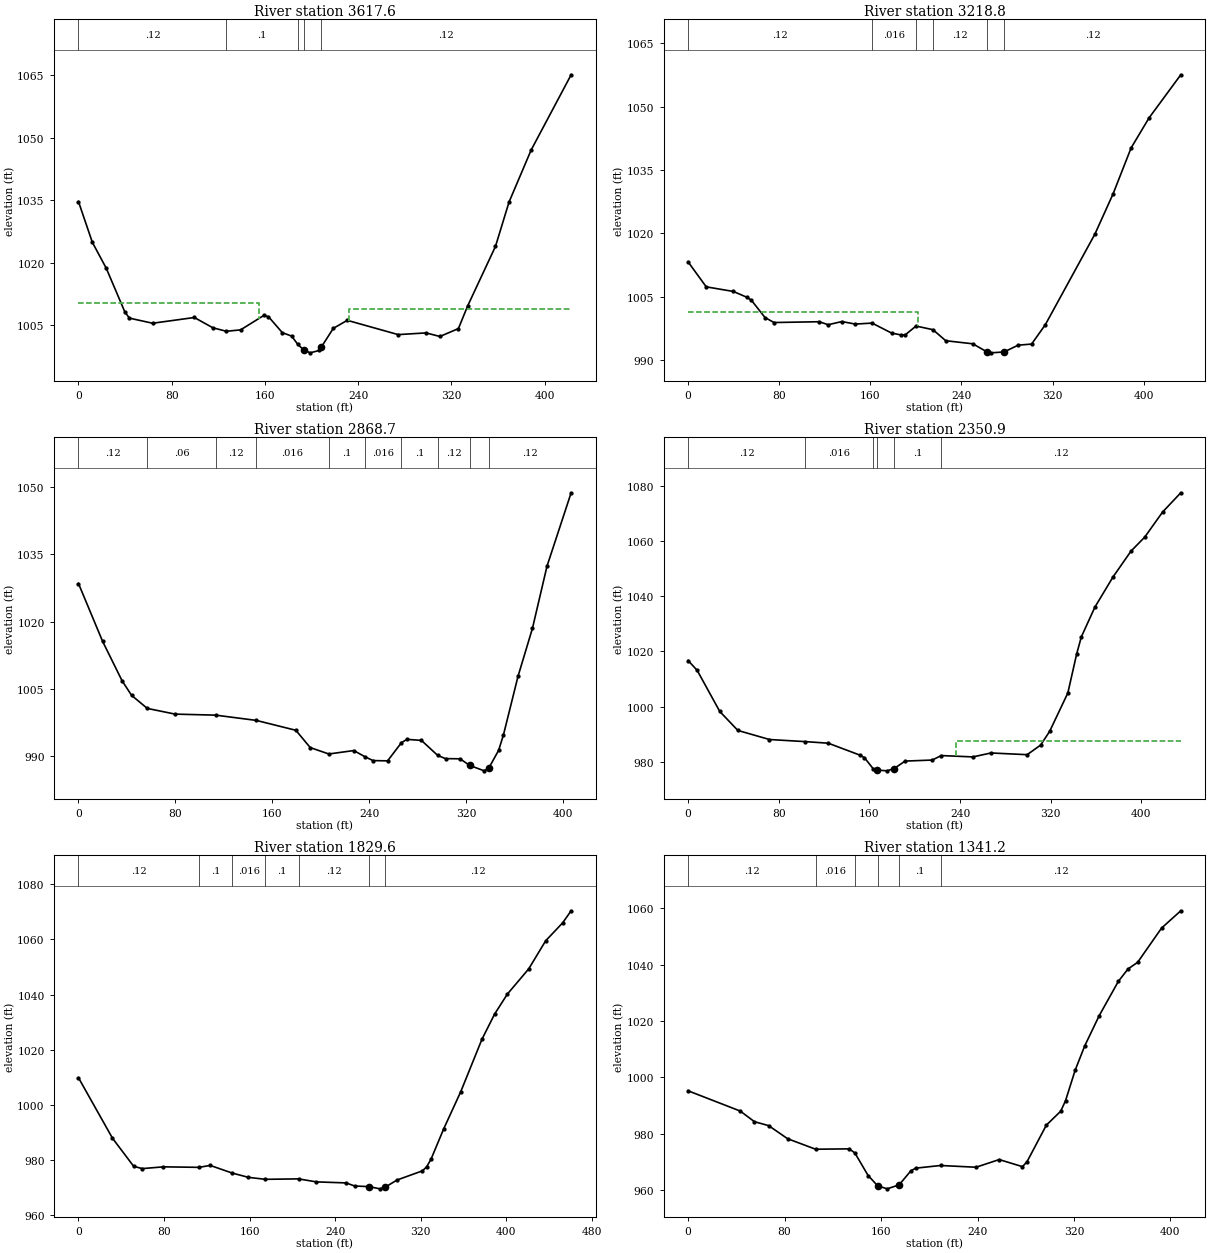
Type RM Length L Ch R = 1 ,3617.6  ,407.9,398.8,389.2
XS GIS Cut Line= 3
     1792960.629      368560.264     1793057.145      368908.909
     1793094.814      368956.846
#Sta/Elev= 30
       0 1034.65    11.9 1024.86    23.8 1018.66    39.8 1008.13    43.7 1006.66
    63.6 1005.43    99.4 1006.81   115.3 1004.34  126.911003.496   139.1 1003.84
     159  1007.3     163 1007.01   174.9 1003.17   182.9 1002.34   188.21000.341
   193.4  998.98   198.8  998.32   206.7   998.9   208.4  999.72   218.6 1004.19
   230.6 1006.13   274.3  1002.7   298.2 1003.11   310.1 1002.25     326 1004.15
   333.9 1009.58   357.8  1023.9   369.4 1034.53   388.4 1047.05   422.7 1065.12
#Mann= 5 ,-1 , 0
       0     .12       0  126.91      .1       0   188.2     .12       0
   193.4    .045       0   208.4     .12       0
#XS Ineff= 2 , 0
          154.61 1010.19  232.33         1008.76
Permanent Ineff=
       F       F
Bank Sta=193.4,208.4
XS Rating Curve= 0 ,0
Exp/Cntr=0.3,0.1

Type RM Length L Ch R = 1 ,3218.8  ,338.1,350.1,362.1
XS GIS Cut Line= 2
     1792498.744       368677.22     1792777.478      369008.081
#Sta/Elev= 30
       0 1013.24    15.9 1007.34    39.7 1006.25    51.6 1004.87    55.6 1004.15
    67.5 1000.07    75.4  998.89   115.1  999.08     123  998.37     135  999.12
   146.8  998.52   161.5998.7577   178.6   996.4   186.5  995.97   190.5  995.94
  200.12998.0563  214.97997.1943   226.2  994.58     250  993.85   262.5  991.92
   265.9  991.71   277.5  991.92   289.7  993.52   301.6  993.79   313.6  998.35
   357.2 1019.84   373.1 1029.33     389 1040.26   404.8 1047.38   432.6 1057.57
#Mann= 6 ,-1 , 0
       0     .12       0   161.5    .016       0  200.12      .1       0
  214.97     .12       0   262.5    .045       0   277.5     .12       0
#XS Ineff= 2 , 0
          201.81  1001.5
Permanent Ineff=
       F       F
Bank Sta=262.5,277.5
XS Rating Curve= 0 ,0
Exp/Cntr=0.3,0.1

Type RM Length L Ch R = 1 ,2868.7  ,517.7,517.8,517.4
XS GIS Cut Line= 2
     1792322.992      368715.256     1792390.807      369115.942
#Sta/Elev= 30
       0 1028.49    19.9 1015.57    35.9  1006.8    43.8 1003.51   56.741000.596
    79.7  999.32   113.2999.0892  146.61997.9196   179.3  995.71   191.2  991.84
  206.52990.4159   227.1  991.18  236.48989.7757     243  988.94     255  988.88
  266.43992.9418   270.9  993.68   282.9  993.45  296.39990.0781   302.8  989.38
   314.8  989.34   322.7  987.86   334.7  986.65   338.6  987.33   346.6  991.23
   350.6  994.71   362.6 1007.78   374.5 1018.49   386.5 1032.37   406.4 1048.76
#Mann= 10 ,-1 , 0
       0     .12       0   56.74     .06       0   113.2     .12       0
  146.61    .016       0  206.52      .1       0  236.48    .016       0
  266.43      .1       0  296.39     .12       0   322.7    .045       0
   338.6     .12       0
Bank Sta=322.7,338.6
XS Rating Curve= 0 ,0
Exp/Cntr=0.3,0.1

Type RM Length L Ch R = 1 ,2350.9  ,523.8,521.3,518.4
XS GIS Cut Line= 2
     1791853.895      368816.777     1791926.451      369245.473
#Sta/Elev= 30
       0 1016.72       8 1013.13    27.9  998.26    43.9  991.36    71.8  988.07
  103.57987.3046   123.7  986.73   151.6  982.41   155.6  981.48  163.48977.3879
   166.8     977   175.5  976.71   181.8  977.53   191.5  980.25   215.4  980.62
  223.39982.2478   251.3  981.76   267.3  983.19   299.2  982.57   311.1  986.05
   319.1  991.06   335.1 1004.92     343 1019.26     347 1025.27     359 1036.09
     375 1047.04   390.9 1056.42   402.9 1061.44   418.8  1070.6   434.8 1077.56
#Mann= 6 ,-1 , 0
       0     .12       0  103.57    .016       0  163.48      .1       0
   166.8    .045       0   181.8      .1       0  223.39     .12       0
#XS Ineff= 2 , 0
                          236.57          987.43
Permanent Ineff=
       F       F
Bank Sta=166.8,181.8
XS Rating Curve= 0 ,0
Exp/Cntr=0.3,0.1

Type RM Length L Ch R = 1 ,1829.6  ,492.6,488.4,479.5
XS GIS Cut Line= 2
     1791345.648      368929.593     1791485.034      369368.605
#Sta/Elev= 30
       0 1009.76    31.8   987.8    51.6   977.6    59.6  976.77    79.4  977.41
  112.74977.2238   123.1  977.93  143.73975.1508   158.8   973.6  174.71972.8797
  205.71973.0358   222.4  971.95   250.2  971.57   258.1  970.46   271.7  970.22
   281.9  969.42   286.7  970.01   297.8  972.62   321.6  975.96   325.6  977.46
   329.6  980.18   341.5  991.25   357.4  1004.7   377.2 1023.73   389.1 1032.92
     401 1040.16   420.9 1049.29   436.8 1059.51   452.7 1066.04   460.6 1070.41
#Mann= 7 ,-1 , 0
       0     .12       0  112.74      .1       0  143.73    .016       0
  174.71      .1       0  205.71     .12       0   271.7    .045       0
   286.7     .12       0
Bank Sta=271.7,286.7
XS Rating Curve= 0 ,0
Exp/Cntr=0.3,0.1

Type RM Length L Ch R = 1 ,1341.2  ,342,339.3,341.2
XS GIS Cut Line= 4
     1790904.007      369147.932     1790985.141      369322.577
     1791056.755       369374.66     1791107.457      369491.664
#Sta/Elev= 30
       0  995.26    43.2  988.08      55   984.3    66.8   982.9    82.5  978.26
  105.72974.5319   133.6  974.66  138.29973.2084   149.3  965.18   157.2  961.55
   165.1  960.47     175  961.89   184.7  966.84   188.6   967.8  209.31968.7552
   238.8  968.14     258  970.86   277.3  968.34   281.1  970.12   297.1  983.08
     309  988.01     313  991.74     321 1002.58   328.9 1011.18   340.9 1021.91
   356.8 1034.09   364.8  1038.5   372.8 1040.86   392.7 1053.04   408.6 1059.16
#Mann= 6 ,-1 , 0
       0     .12       0  105.72    .016       0  138.29      .1       0
   157.2    .045       0     175      .1       0  209.31     .12       0
Bank Sta=157.2,175
XS Rating Curve= 0 ,0
Exp/Cntr=0.3,0.1

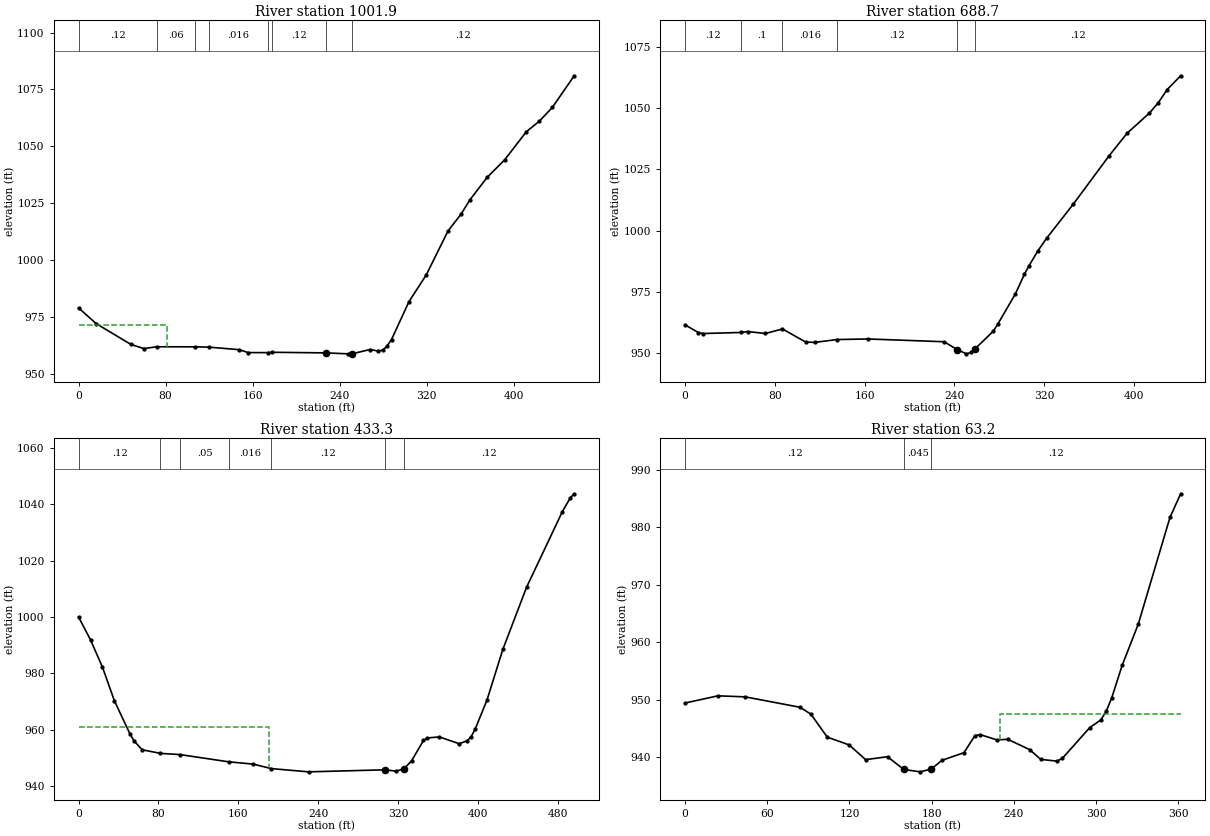
Type RM Length L Ch R = 1 ,1001.9  ,314.7,313.2,311.5
XS GIS Cut Line= 2
     1790593.202      369301.589     1790841.119      369684.019
#Sta/Elev= 30
       0  979.04      16  972.21      48  963.04      60   961.2   71.96961.9986
  107.15961.9711  119.74961.8432   147.9   960.7   155.9  959.44  174.04959.4242
  177.55 959.579   227.9   959.3   247.9  958.89   251.9  958.96   267.9  960.77
   275.8  960.12   279.8  960.54   283.8  962.39   287.8  965.17   303.8  981.78
   319.8  993.59   339.8  1012.9   351.8 1020.25   359.8 1026.44   375.8 1036.42
   391.8 1044.06   411.8 1056.42   423.8 1061.08   435.8 1067.14   455.8    1081
#Mann= 8 ,-1 , 0
       0     .12       0   71.96     .06       0  107.15      .1       0
  119.74    .016       0  174.04      .1       0  177.55     .12       0
   227.9    .045       0   251.9     .12       0
#XS Ineff= 2 , 0
           81.12  971.43
Permanent Ineff=
       F       F
Bank Sta=227.9,251.9
XS Rating Curve= 0 ,0
Exp/Cntr=0.3,0.1

Type RM Length L Ch R = 1 ,688.7   ,262.1,255.4,248.4
XS GIS Cut Line= 2
     1790310.757      369470.002     1790577.175      369822.159
#Sta/Elev= 30
       0  961.66    11.9  958.53    15.9  958.14   49.72958.5668    55.7  958.94
    71.6  958.15   86.76959.9993   107.4  954.68   115.4  954.52  135.51955.6832
   163.1  955.92   230.7  954.79   242.7  951.56   250.6  949.86   254.6  950.41
   258.6     952   274.5  959.03   278.5  961.84   294.4  974.34   302.3  982.23
   306.3  985.61   314.3  991.77   322.2  996.98   346.1 1010.95   377.9  1030.6
   393.8  1039.7   413.7 1047.92   421.7 1052.18   429.6 1057.55   441.6 1063.16
#Mann= 6 ,-1 , 0
       0     .12       0   49.72      .1       0   86.76    .016       0
  135.51     .12       0   242.7    .045       0   258.6     .12       0
Bank Sta=242.7,258.6
XS Rating Curve= 0 ,0
Exp/Cntr=0.3,0.1

Type RM Length L Ch R = 1 ,433.3   ,361.8,370.1,376.5
XS GIS Cut Line= 2
     1790031.813      369654.857     1790427.382      369955.116
#Sta/Elev= 30
       0  999.95    11.9  991.87    23.8  982.25    35.8   970.3    51.6  958.37
    55.6  956.01    63.6  952.88   82.03951.6043  101.81951.1592  150.66948.5902
   174.8   947.8  193.28946.1923   230.4  945.05     307  945.77   317.8  945.31
   325.8  946.04   333.7  948.98   345.6  956.19   349.6  957.08   361.5  957.44
   381.4  955.03   389.4  956.07   393.3  957.49   397.3  960.15   409.2  970.48
   425.1  988.48   448.9 1010.54   484.7 1037.32   492.6 1042.18   496.6  1043.7
#Mann= 7 ,-1 , 0
       0     .12       0   82.03     .06       0  101.81     .05       0
  150.66    .016       0  193.28     .12       0     307    .045       0
   325.8     .12       0
#XS Ineff= 2 , 0
           190.5  960.86
Permanent Ineff=
       F       F
Bank Sta=307,325.8
XS Rating Curve= 0 ,0
Exp/Cntr=0.3,0.1

Type RM Length L Ch R = 1 ,63.2    ,68.5,63.2,59.7
XS GIS Cut Line= 3
     1789926.737      369936.705     1790122.754      370173.593
     1790171.317      370197.967
#Sta/Elev= 30
       0  949.42      24  950.67    43.9  950.49    83.9  948.68    91.8  947.49
   103.8  943.49   119.8  942.13   131.8  939.57   147.8  940.08   159.7  937.86
   171.7  937.45   179.7  937.94   187.7  939.47   203.6  940.78   211.6  943.74
   215.6  943.92   227.6     943   235.6  943.11   251.6  941.31   259.6  939.62
   271.5  939.31   275.5  939.81   295.5  945.16   303.5  946.47   307.5     948
   311.4  950.25   319.1  955.97   330.8  963.09     354  981.69   361.8  985.81
#Mann= 3 ,-1 , 0
       0     .12       0   159.7    .045       0   179.7     .12       0
#XS Ineff= 2 , 0
                          230.19          947.43
Permanent Ineff=
       F       F
Bank Sta=159.7,179.7
XS Rating Curve= 0 ,0
Exp/Cntr=0.3,0.1

Chan Stop Cuts=-1
Use User Specified Reach Order=0
Composite Channel Slope=5